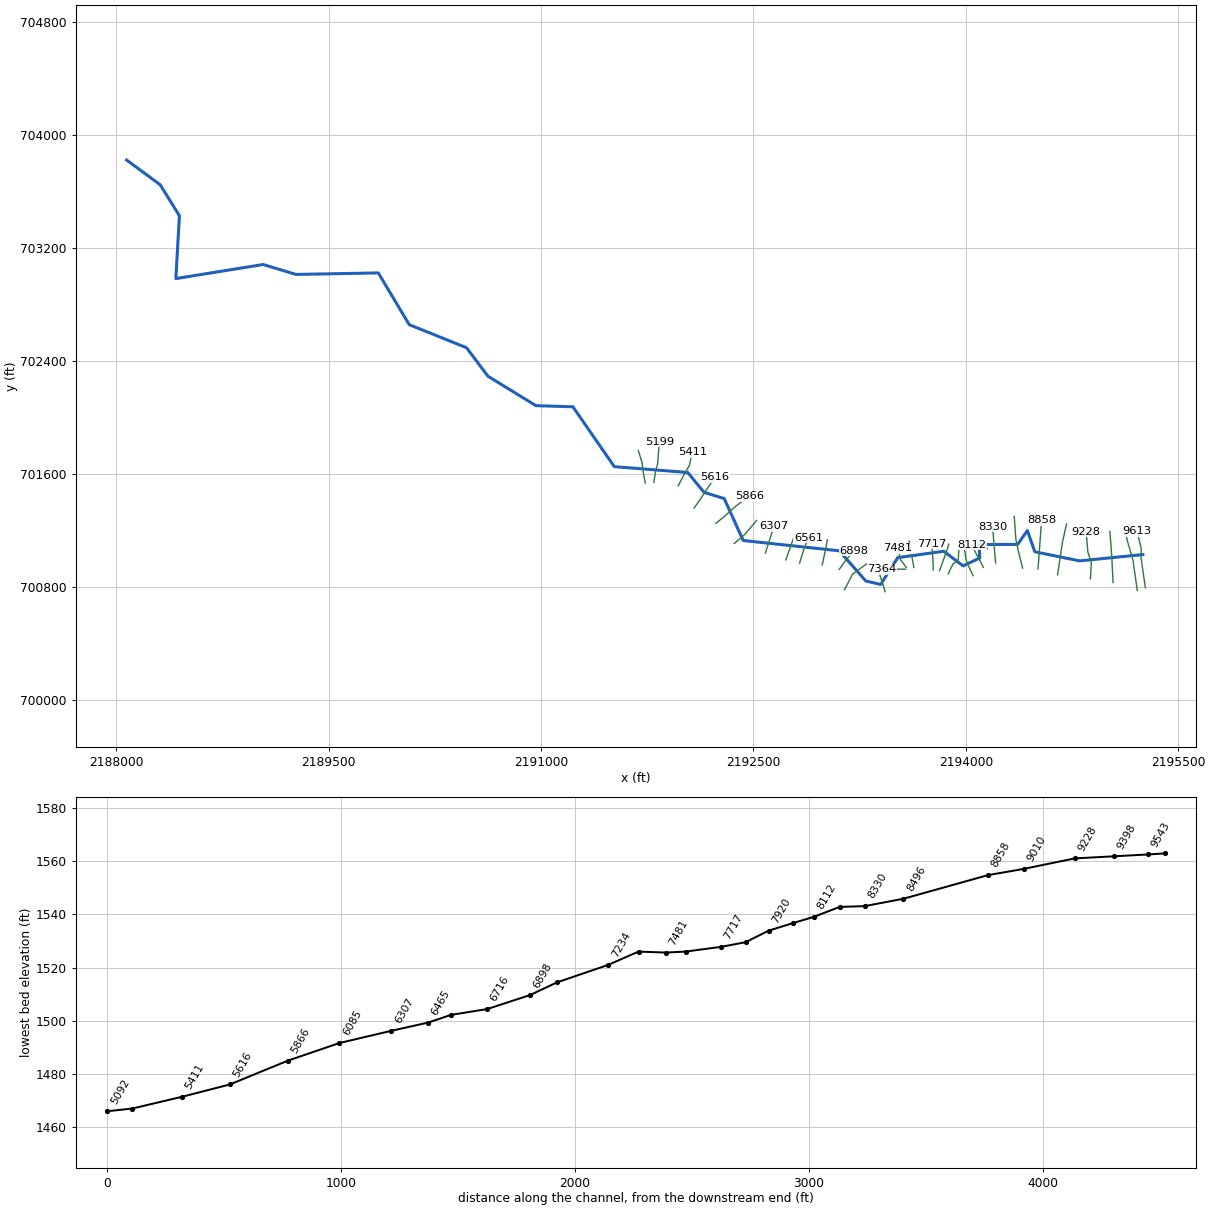
--- TRUBIERN.prj (project) ---

Proj Title=TRUBIERN
Current Plan=p01
Default Exp/Contr=0,0
English Units
Geom File=g01
Flow File=f01
Plan File=p01
BEGIN DESCRIPTION:
-------- MODELED AS PART OF WVEMD CTP PROGRAM, 2023----------
Stream Name: Trubie Run
Flood Zone:  AFH
Upshur County, WV
HEC-RAS Version: RAS 6.3
Vertical Datum: NAVD88
Projection: NAD 1983 StatePlane West Virginia S FIPS 4702 (US Feet)
Terrain: 1-meter LIDAR (FEMA Region III 3DEP collected 2016-2018)
Land Use: 2019 NLCD
Hydrologic Method:
WV SIR2010-5033 regression equations
Additional Model Notes:
None
END DESCRIPTION:
DSS Export Rating Curves= 0
DSS Export Rating Curve Sorted= 0
DSS Export Volume Flow Curves= 0
DXF OffsetX= 0
DXF OffsetY= 0
DXF ScaleX= 0
DXF ScaleY= 0

--- TRUBIERN.p01 (plan) ---

Plan Title=Floodplain
Program Version=4.00
Geom File=g01
Flow File=f01
K Sum by GR=0
Std Step Tol=0.01
Critical Tol=0.01
Num of Std Step Trials=20
Max Error Tol=0.3
Flow Tol Ratio=0.001
Split Flow NTrial=30
Split Flow Tol=0.02
Split Flow Ratio=0.02
Log Output Level=0
Friction Slope Method=1
Unsteady Friction Slope Method=2
Unsteady Bridges Friction Slope Method=1
Global Log Level=0
CheckData=False
Run HTab=0
Run UNet=0
Run PostProcess=0
UNET Theta=0
UNET Theta Warmup=0
UNET ZTol=0
UNET ZSATol=0
UNET MxIter=0
UNET MaxInSteps=0
UNET DtIC=0
UNET DtMin=0
UNET MaxCRTS=0
UNET WFStab=0
UNET SFStab=0
UNET WFX=0
UNET SFX=0
UNET DSS MLevel=0
UNET DZMax Abort=0
UNET Convert EG Bridges=0
UNET Use Existing IB Tables=0
UNET Froude Limit=0
UNET Froude Power=0
Write IC File=0
Echo Input=False
Echo Output=False
Write Detailed=0

--- TRUBIERN.f01 (steady flow) ---

Flow Title=Flows
Program Version=6.30
Number of Profiles= 1
Profile Names=01pct
River Rch & RM=TRUBIERN,Main,9613
     403
River Rch & RM=TRUBIERN,Main,5866
     632
River Rch & RM=TRUBIERN,Main,2530
     781
Boundary for River Rch & Prof#=TRUBIERN,Main            , 1
Up Type= 0
Dn Type= 3
Dn Slope=0.002084
DSS Import GetInterval= 0
DSS Import GetPeak= 0
DSS Import FillOption= 0

--- TRUBIERN.g01 (geometry) ---

Geom Title=Geometry
Program Version=6.30

River Reach=TRUBIERN        ,Main
Reach XY= 30
2195250.99117776701029.351001604     2194803.858      700984.513
     2194488.048      701049.158     2194435.022      701199.165
     2194366.714      701101.297     2194095.288      701100.381
     2194098.636       701005.06     2193981.452      700949.258
     2193844.179      701052.678     2193519.641      701007.578
     2193399.223      700817.708     2193294.516      700841.861
     2193106.191      701055.825     2192428.069      701128.912
     2192293.629      701425.978     2192151.176      701470.162
     2192035.995      701610.554     2191517.581      701651.962
     2191225.207      702075.714     2190963.825      702083.926
     2190625.494      702292.082     2190473.312      702494.257
     2190068.848      702657.513     2189850.533      703023.946
     2189268.419      703013.244     2189037.141      703083.497
     2188420.401      702983.855     2188445.698      703428.839
     2188309.712       703648.27     2188072.597      703823.431

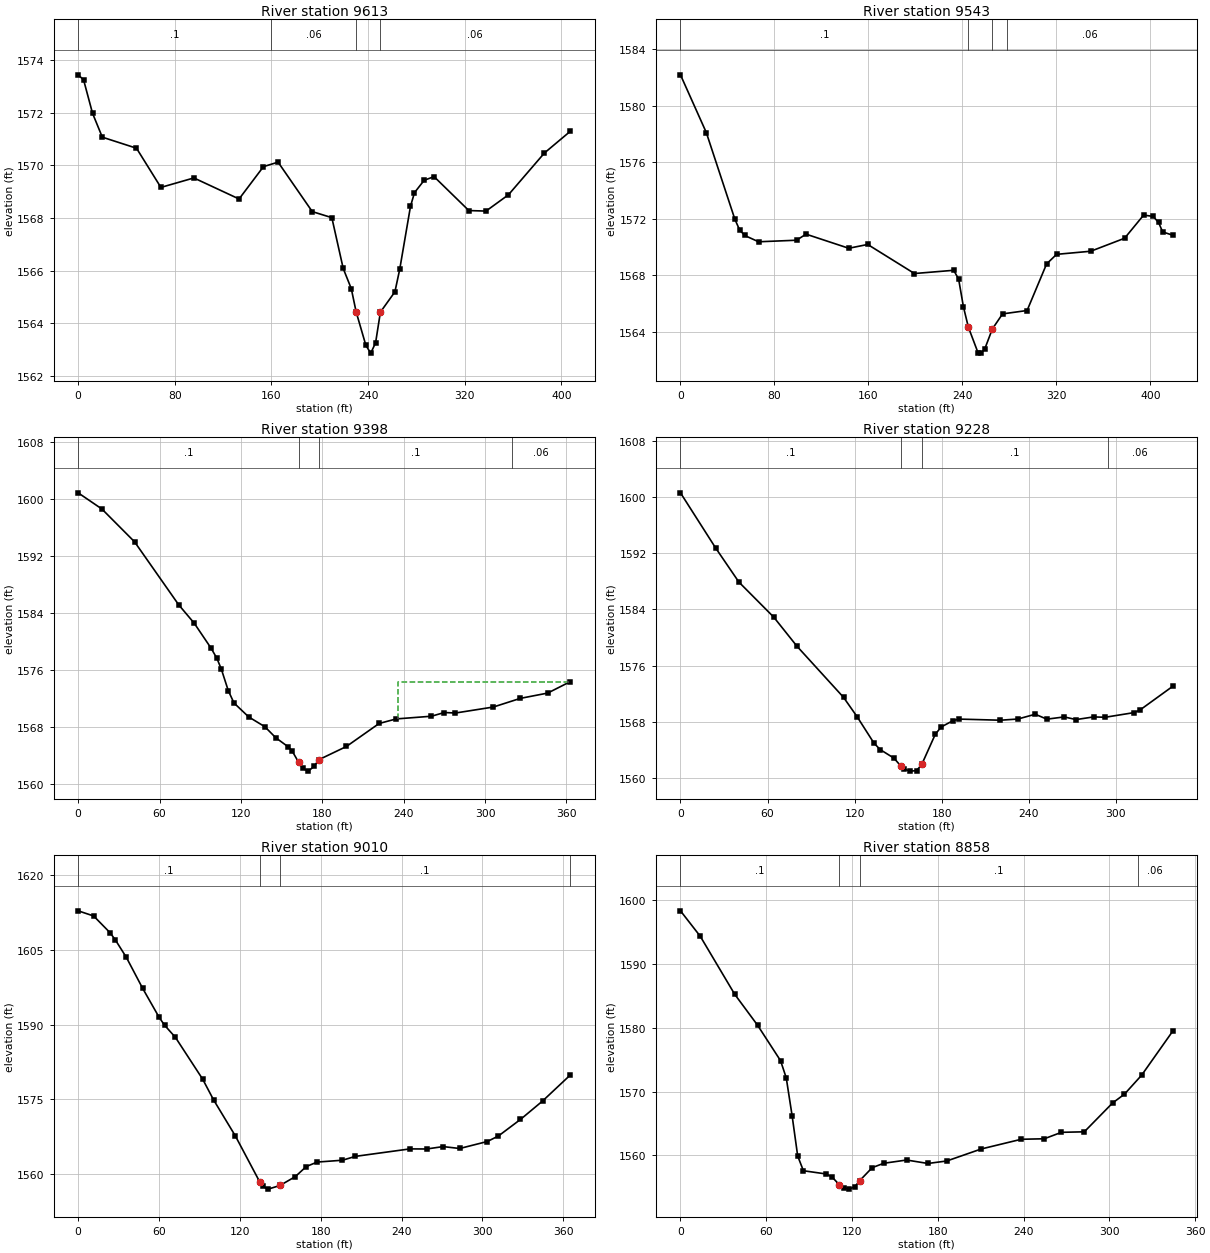
Type RM Length L Ch R = 1 ,9613    ,69.8,69.8,69.8
XS GIS Cut Line= 4
2195268.81591049700793.3547540052195236.58670665701017.134896835
 2195239.4404068701069.3576095682195210.31412173701194.958881841
#Sta/Elev= 30
       0 1573.44     4.5 1573.25    11.9 1571.98      20 1571.07    48.3 1570.65
    68.5 1569.16    95.8 1569.52   133.2 1568.72   153.4 1569.95   165.5 1570.12
   193.8 1568.24     210 1568.01   219.4 1566.08   226.1 1565.31   230.1 1564.43
   238.2 1563.15   242.2 1562.86   246.2 1563.25   250.2 1564.42   262.2 1565.19
   266.2 1566.05   275.1 1568.44   278.4 1568.96   286.4 1569.43   294.6 1569.57
   323.4 1568.28   337.6 1568.26   356.2 1568.88     386 1570.47   407.3 1571.29
#Mann= 4 ,-1,0
       0      .1       0     160     .06       0   230.1    .045       0
   250.2     .06       0
Bank Sta=230.1,250.2
XS Rating Curve= 0 ,0
Exp/Cntr(USF)=0,0
Exp/Cntr=0.3,0.1

Type RM Length L Ch R = 1 ,9543    ,147.9,145.4,141.6
XS GIS Cut Line= 4
2195211.66025813700775.3602283292195180.87410512700990.990025284
2195138.98851994701135.0451219852195130.82160386701185.467237916
#Sta/Elev= 30
       0 1582.19      22  1578.1    46.3 1571.96    50.3 1571.21    54.6 1570.81
    66.5 1570.36    98.8 1570.47   106.9  1570.9   143.3  1569.9   159.4 1570.17
   199.2 1568.11   232.6 1568.34   236.8 1567.72   240.9 1565.75   245.1 1564.31
   253.4 1562.48   255.6 1562.47   258.9 1562.73   265.5 1564.18   274.2 1565.25
   295.1 1565.49   311.7 1568.79   320.2 1569.47   349.3 1569.69   378.1 1570.61
   394.3 1572.25   402.4 1572.16     407 1571.73   410.5 1571.06   418.9 1570.83
#Mann= 4 ,-1,0
       0      .1       0   245.1    .045       0   265.5      .1       0
  277.82     .06       0
Bank Sta=245.1,265.5
XS Rating Curve= 0 ,0
Exp/Cntr=0.3,0.1

Type RM Length L Ch R = 1 ,9398    ,165.3,169.5,171.5
XS GIS Cut Line= 3
2195040.26828817700831.653987222     2195032.319      701001.486
2195018.10833225701193.772426351
#Sta/Elev= 30
       0 1600.86    17.5 1598.59    41.6 1593.98    74.2 1585.12    85.6 1582.55
    98.1 1579.02   102.3 1577.62   105.6 1576.09   110.7 1573.08   114.9 1571.35
   125.7  1569.4   137.7 1568.01   145.7 1566.47   154.6 1565.23   157.7 1564.64
   162.51563.038   165.7 1562.15   169.7 1561.78   173.9 1562.44   177.51563.387
   197.8 1565.24   221.9 1568.47   234.5 1569.11   260.5 1569.49     270 1570.01
   278.2 1569.94   306.1 1570.78   326.1    1572   346.2 1572.74   362.8 1574.34
#Mann= 4 ,-1,0
       0      .1       0   162.5    .045       0   177.5      .1       0
  320.02     .06       0
#XS Ineff= 2 , 0
                        236.1418         1574.34
Permanent Ineff=
       F       T
Bank Sta=162.5,177.5
XS Rating Curve= 0 ,0
Exp/Cntr=0.3,0.1

Type RM Length L Ch R = 1 ,9228    ,223.5,218.3,212.2
XS GIS Cut Line= 4
2194880.48969747700856.9728342412194887.11900647700972.322810836
2194862.59056317701047.2340025332194849.63165258701191.399515369
#Sta/Elev= 30
       0 1600.56    24.2 1592.73    40.3 1587.86    64.3 1582.88    80.3 1578.74
   112.4 1571.47   121.7 1568.73   133.3 1564.98   137.6 1564.05   147.1 1562.83
   151.91561.701   154.3 1561.25   158.5 1560.98   162.7 1561.05   166.31561.935
   175.6 1566.21   179.6 1567.25     188 1568.18   192.2 1568.38   220.5 1568.22
   232.5 1568.39   244.5 1569.07   252.5 1568.37   264.5 1568.69   272.6 1568.31
   284.7 1568.69   292.7 1568.64   312.8 1569.31   316.8 1569.69   339.1 1573.02
#Mann= 4 ,-1,0
       0      .1       0   151.9    .045       0   166.3      .1       0
  294.37     .06       0
Bank Sta=151.9,166.3
XS Rating Curve= 0 ,0
Exp/Cntr(USF)=0,0
Exp/Cntr=0.3,0.1

Type RM Length L Ch R = 1 ,9010    ,151,152.1,152.9
XS GIS Cut Line= 3
2194648.39022349700885.7734988952194683.74653815701120.745673441
2194711.73695393701245.229364658
#Sta/Elev= 30
       0 1612.78    11.5 1611.75    23.7 1608.39    27.7 1606.92    35.8 1603.45
    47.9 1597.24    60.1 1591.45    64.1 1589.88    72.2 1587.43    92.4 1579.07
   100.5 1574.92   116.7 1567.68     1351558.364   136.9 1557.58     141 1557.03
   149.8 1557.76   161.2 1559.54   169.3 1561.55   177.4 1562.45   196.2 1562.82
   205.7 1563.59   246.3 1565.09   258.6 1565.07   270.9 1565.55   283.2 1565.17
   303.7 1566.57   311.9 1567.67   328.3 1570.99   344.7 1574.68   365.2 1579.87
#Mann= 4 ,-1,0
       0      .1       0     135    .045       0   149.8      .1       0
  365.21     .06       0
Bank Sta=135,149.8
XS Rating Curve= 0 ,0
Exp/Cntr(USF)=0,0
Exp/Cntr=0.3,0.1

Type RM Length L Ch R = 1 ,8858    ,354.9,361.7,361.6
XS GIS Cut Line= 2
2194510.43774871700927.3862807642194535.48180493701270.637168972
#Sta/Elev= 30
       0 1598.31    13.8 1594.34    37.9 1585.25    53.9  1580.4      70 1574.84
      74 1572.14    78.1 1566.22      82  1559.9      86 1557.59   102.1 1557.08
   106.1 1556.59     1111555.431   114.1 1554.87   118.1 1554.71   122.1 1555.12
   125.41556.042   134.1 1558.07   142.2 1558.76   158.2 1559.27   173.1 1558.73
   186.3 1559.12   210.4    1561   238.4 1562.52   254.5  1562.6   266.5 1563.61
   282.5 1563.69   302.3 1568.21   310.6 1569.59   322.6 1572.56   344.2 1579.41
#Mann= 4 ,-1,0
       0      .1       0     111    .045       0   125.4      .1       0
     320     .06       0
Bank Sta=111,125.4
XS Rating Curve= 0 ,0
Exp/Cntr(USF)=0,0
Exp/Cntr=0.3,0.1

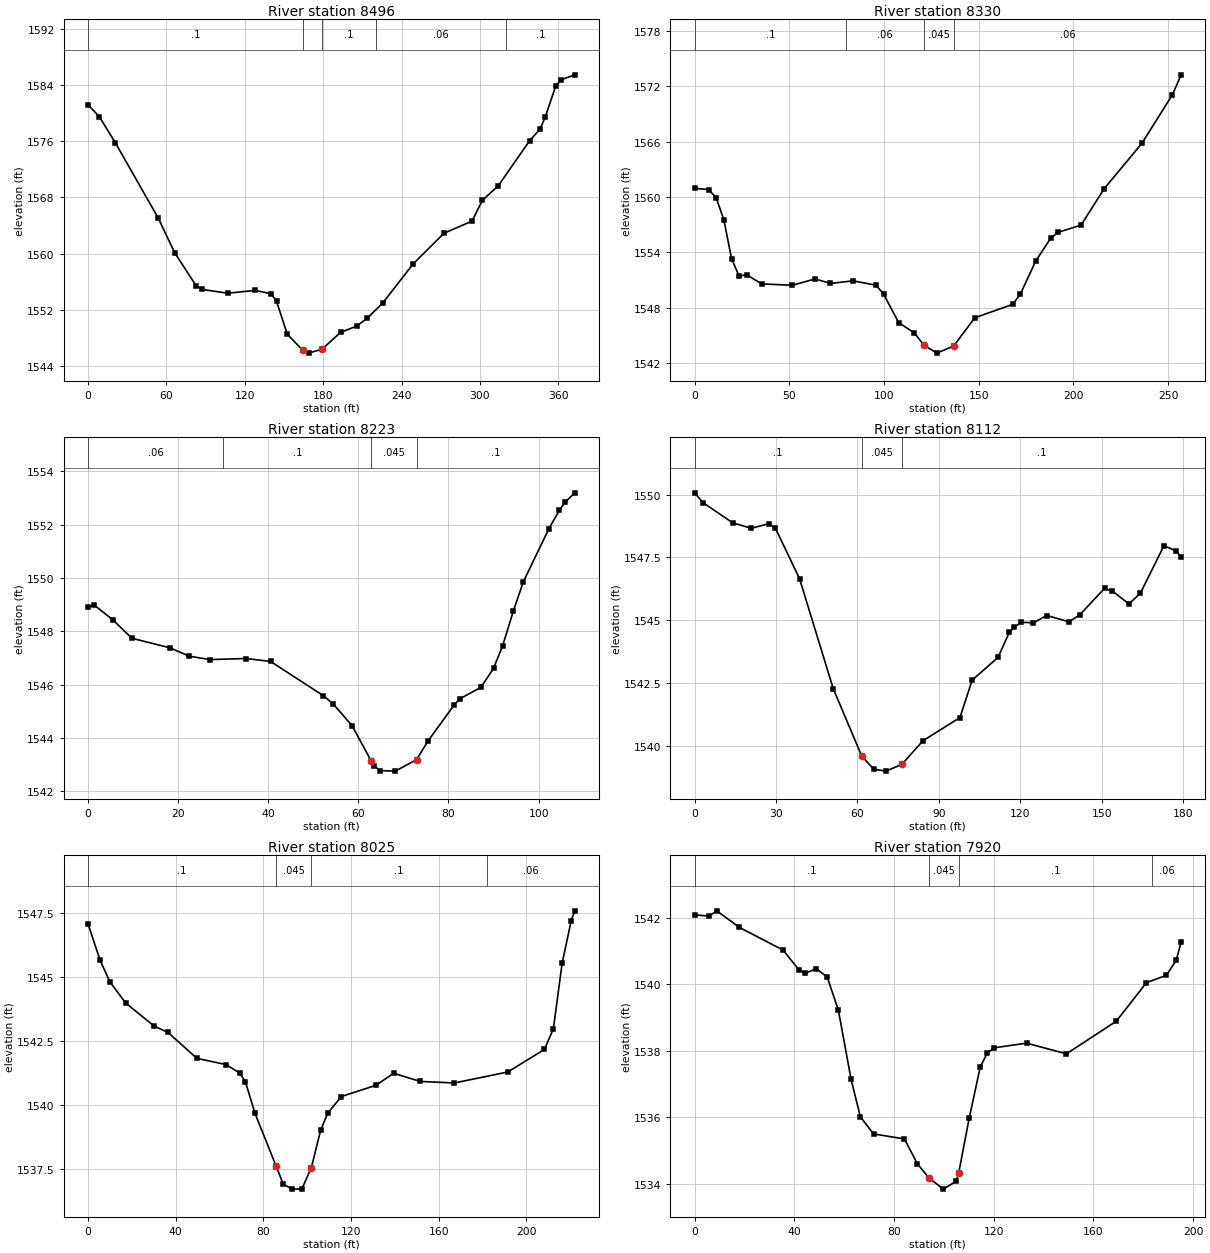
Type RM Length L Ch R = 1 ,8496    ,167.2,166.1,164.2
XS GIS Cut Line= 4
2194401.34060184700932.9516265912194370.24013986701058.990340907
2194353.87147566701137.5599290522194342.41341073701299.609704601
#Sta/Elev= 30
       0 1581.19     8.5 1579.53    20.8 1575.81    53.8 1565.03    66.2 1560.16
    82.6 1555.45    87.1 1554.91   106.9 1554.36     128 1554.77   140.2 1554.28
   144.3  1553.2   152.5 1548.52   164.41546.223   168.8 1545.83   179.11546.395
   193.3 1548.78   205.6 1549.68   213.7  1550.8   225.7 1552.99   248.8 1558.53
   272.6 1562.92   293.9 1564.63   301.9  1567.6     314 1569.66     338 1576.07
     346 1577.73   349.9 1579.41   358.1  1583.9   362.1 1584.75   372.5 1585.47
#Mann= 5 ,-1,0
       0      .1       0   164.4    .045       0   179.1      .1       0
  220.08     .06       0  320.08      .1       0
Bank Sta=164.4,179.1
XS Rating Curve= 0 ,0
Exp/Cntr(USF)=0,0
Exp/Cntr=0.3,0.1

Type RM Length L Ch R = 1 ,8330    ,102.9,107,111.8
XS GIS Cut Line= 4
2194211.18052872700969.7778960732194203.74290144701050.808887968
2194198.65399857 701114.615900912194189.65055503701225.788855973
#Sta/Elev= 30
       0 1560.93     7.4 1560.81    11.4 1559.91    15.5  1557.5    19.5 1553.32
    23.5 1551.43    27.5 1551.56    35.5 1550.57    51.6 1550.42    63.7 1551.11
    71.7 1550.62    83.7  1550.9    95.8 1550.43    99.8 1549.47   107.8 1546.36
   115.9 1545.28   121.11543.931   127.9 1543.06   136.8 1543.83     148  1546.9
     168 1548.35     172 1549.45   180.1 1553.04   188.1 1555.54   192.1 1556.17
   204.1 1556.95   216.2 1560.87   236.2 1565.82   252.3 1571.08   256.9 1573.25
#Mann= 4 ,-1,0
       0      .1       0      80     .06       0   121.1    .045       0
   136.8     .06       0
Bank Sta=121.1,136.8
XS Rating Curve= 0 ,0
Exp/Cntr(USF)=0,0
Exp/Cntr=0.3,0.1

Type RM Length L Ch R = 1 ,8223    ,113.5,111,105.1
XS GIS Cut Line= 4
2194153.38430964701072.2099129142194101.86029679701089.605600624
2194081.66595628701120.7625831272194073.24691946701134.967271127
#Sta/Elev= 29
       0  1548.9     1.3 1548.99     5.5 1548.43     9.7 1547.74    18.2 1547.38
    22.4 1547.07      27 1546.94    35.1 1546.98    40.5 1546.87    52.2 1545.59
    54.4 1545.28    58.6 1544.46    62.91543.125    63.4 1542.97    64.8 1542.78
    68.2 1542.76    72.9 1543.19    75.5  1543.9    81.3 1545.25    82.5 1545.47
    87.2  1545.9      90 1546.61      92 1547.45    94.4 1548.76    96.6 1549.85
   102.3 1551.85   104.6 1552.53   105.9 1552.84     108 1553.19
#Mann= 4 ,-1,0
       0     .06       0      30      .1       0    62.9    .045       0
    72.9      .1       0
Bank Sta=62.9,72.9
XS Rating Curve= 0 ,0
Exp/Cntr(USF)=0,0
Exp/Cntr=0.3,0.1

Type RM Length L Ch R = 1 ,8112    ,89,87.7,86.3
XS GIS Cut Line= 4
2194124.08386326700938.3460766642194107.90338342700971.734368412
2194069.63526441701042.877113135 2194044.4656291701098.866710065
#Sta/Elev= 30
       0 1550.07     3.1 1549.68      14 1548.88    20.9 1548.66    27.3 1548.84
    29.8 1548.66    38.7 1546.65    51.1 1542.28    61.6  1539.6      66 1539.08
    70.5    1539    76.4 1539.27    84.2 1540.21    97.8 1541.13   102.3 1542.62
   111.8 1543.52     116 1544.52   117.9 1544.73   120.4 1544.92   124.8  1544.9
   129.8 1545.19     138 1544.94   141.9 1545.21   151.1 1546.27     154 1546.16
   160.1 1545.65   164.3 1546.08     173 1547.97   177.4 1547.76   179.3 1547.52
#Mann= 3 ,-1,0
       0      .1       0    61.6    .045       0    76.4      .1       0
Bank Sta=61.6,76.4
XS Rating Curve= 0 ,0
Exp/Cntr(USF)=0,0
Exp/Cntr=0.3,0.1

Type RM Length L Ch R = 1 ,8025    ,116.6,105,88.2
XS GIS Cut Line= 4
2194051.47292422700880.2260683942194019.61868259700947.657774697
2194002.65733315700991.9227598162193986.93705806701090.795016296
#Sta/Elev= 30
       0 1547.06     5.5 1545.64     9.9 1544.81    17.1 1543.98    30.2 1543.07
    36.4 1542.83    49.7 1541.81      63 1541.57    69.3 1541.23    71.8  1540.9
    76.2 1539.66    85.91537.585   85.92 1537.58    89.1 1536.89    93.3  1536.7
    97.6 1536.71   101.9 1537.54   106.2 1539.02   109.4 1539.67   115.6 1540.32
   131.4 1540.76   139.5 1541.23   151.6 1540.91   167.2 1540.85   191.6 1541.28
   208.3 1542.16   212.4 1542.97   216.4 1545.53   220.5 1547.18   222.1 1547.58
#Mann= 4 ,-1,0
       0      .1       0   85.92    .045       0   101.9      .1       0
  181.98     .06       0
Bank Sta=85.9,101.9
XS Rating Curve= 0 ,0
Exp/Cntr(USF)=0,0
Exp/Cntr=0.3,0.1

Type RM Length L Ch R = 1 ,7920    ,92.2,98.2,103.8
XS GIS Cut Line= 4
2193876.42021012700893.1482854672193908.25376717700959.831210245
2193946.45403564  700991.66476732193951.48038675701063.038953118
#Sta/Elev= 30
       0 1542.09     5.8 1542.05     8.9 1542.21      18 1541.71    35.5 1541.03
    41.8 1540.44    44.4 1540.33    48.8 1540.47    53.2 1540.22    57.7 1539.22
    62.8 1537.14    66.5 1536.02    71.8  1535.5    84.2 1535.35    89.4  1534.6
      94 1534.18    99.8 1533.84     105 1534.08     106 1534.34   110.2 1535.98
   114.6 1537.51   117.4 1537.93   120.2 1538.09   133.2 1538.23   149.2 1537.91
   169.2 1538.89   181.3 1540.05   189.3 1540.27   193.3 1540.73   195.2 1541.27
#Mann= 4 ,-1,0
       0      .1       0      94    .045       0     106      .1       0
  183.62     .06       0
Bank Sta=94,106
XS Rating Curve= 0 ,0
Exp/Cntr(USF)=0,0
Exp/Cntr=0.3,0.1

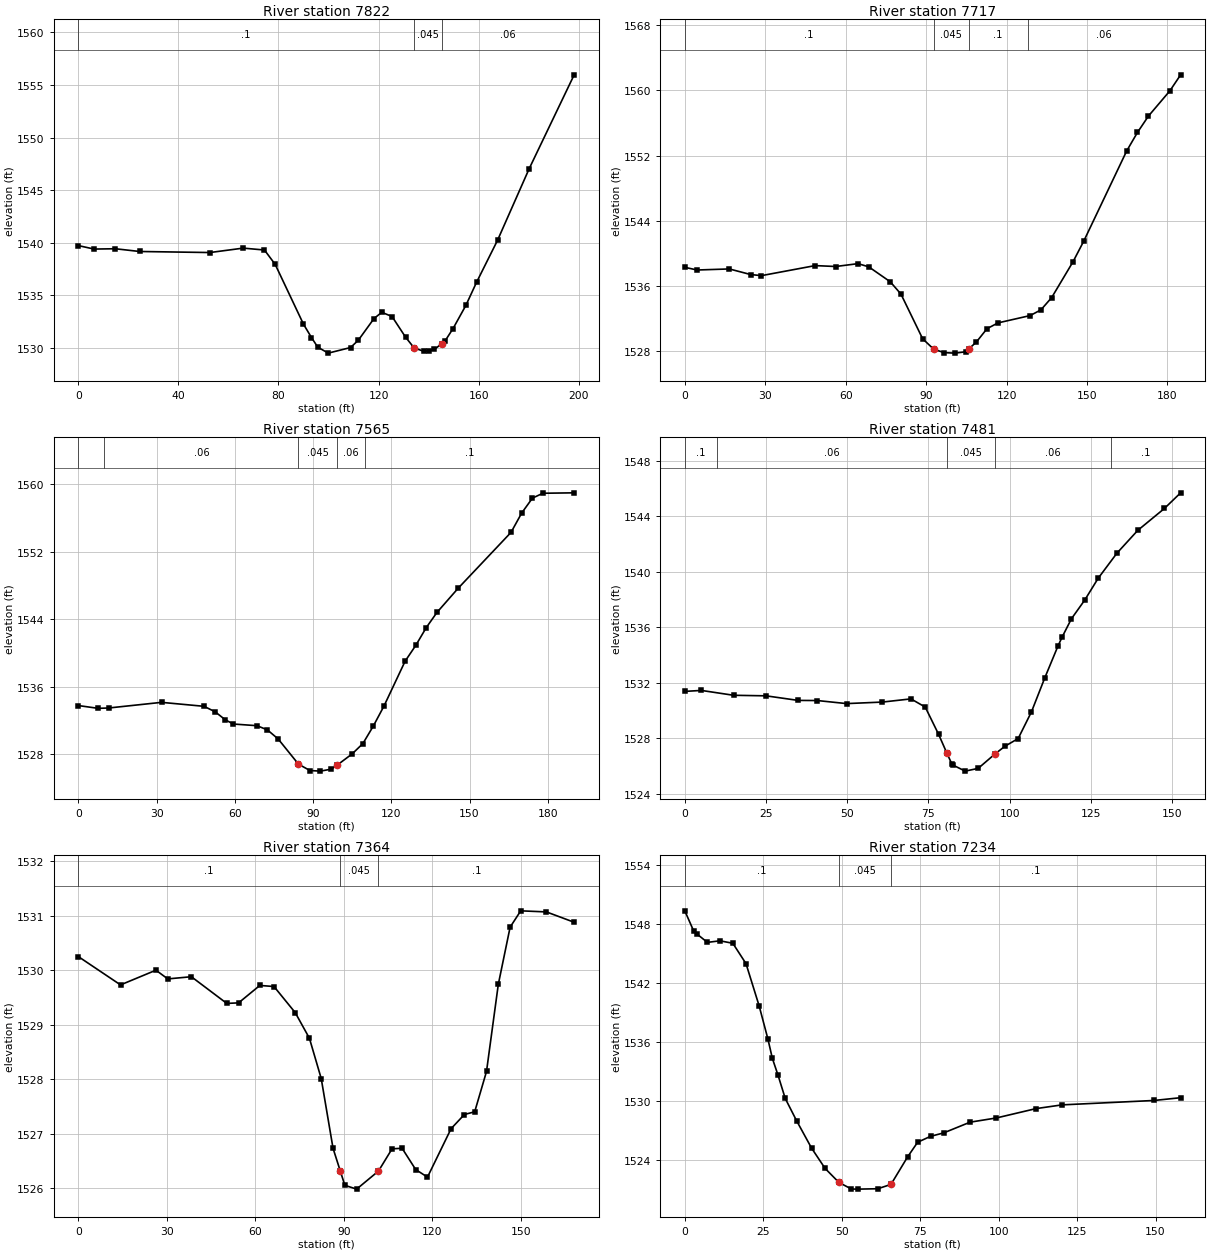
Type RM Length L Ch R = 1 ,7822    ,99.6,104.5,107.8
XS GIS Cut Line= 3
2193814.71316496700915.2542143822193854.42754413701024.468757105
2193880.49010547 701102.24274965
#Sta/Elev= 30
       0 1539.73     6.3  1539.4    14.8 1539.43    24.5 1539.17    52.6 1539.07
    65.9 1539.49    74.4 1539.31    78.7 1537.94      90 1532.26    93.2 1530.99
    95.7 1530.08    99.9 1529.51   108.8 1530.04   111.9 1530.73   118.2  1532.8
   121.3 1533.39   125.4 1532.99   130.8 1531.03   134.21530.013   138.1 1529.68
   140.3 1529.74   142.3 1529.86   145.3 1530.41   146.6 1530.67   149.8 1531.85
   154.9 1534.04   159.2 1536.25   167.6 1540.25   180.2 1547.03   198.2 1555.96
#Mann= 3 ,-1,0
       0      .1       0   134.2    .045       0   145.3     .06       0
Bank Sta=134.2,145.3
XS Rating Curve= 0 ,0
Exp/Cntr(USF)=0,0
Exp/Cntr=0.3,0.1

Type RM Length L Ch R = 1 ,7717    ,150.3,151.9,152.8
XS GIS Cut Line= 4
2193770.40824011700920.6094505132193767.72751952700999.020527891
2193764.37661878 701038.226066582193760.35553788701105.244081433
#Sta/Elev= 30
       0  1538.3     4.6 1537.97    16.6  1538.1    24.6 1537.41    28.6 1537.28
    48.6 1538.51    56.3  1538.4    64.6 1538.75    68.6 1538.36    76.6 1536.53
    80.6 1535.02    88.7 1529.53    92.81528.259    96.7 1527.83   100.7 1527.77
   104.7 1527.93   105.91528.287   108.7 1529.12   112.7 1530.77   116.8 1531.48
   128.8 1532.38   132.8 1533.08   136.8 1534.58   144.8    1539   148.8 1541.53
   164.8 1552.59   168.8 1554.85   172.9 1556.86   180.9 1559.96   184.9 1561.92
#Mann= 4 ,-1,0
       0      .1       0    92.8    .045       0   105.9      .1       0
  127.81     .06       0
Bank Sta=92.8,105.9
XS Rating Curve= 0 ,0
Exp/Cntr(USF)=0,0
Exp/Cntr=0.3,0.1

Type RM Length L Ch R = 1 ,7565    ,83.6,84.1,84.6
XS GIS Cut Line= 2
2193633.49043991700937.733985626 2193600.7028231701125.001720061
#Sta/Elev= 30
       0 1533.77     7.6 1533.44    11.6 1533.48    31.9 1534.15    48.2 1533.68
    52.5 1533.02    56.3 1532.09    59.4 1531.58    68.5 1531.38    72.5 1530.88
    76.6 1529.81    84.41526.819    88.8 1526.06    92.8 1525.99    96.9 1526.22
    99.31526.716     105 1528.04   109.1 1529.26   113.1 1531.34   117.2 1533.72
   125.3 1539.04   129.4 1540.92   133.4 1543.02   137.5 1544.82   145.6 1547.68
   165.9 1554.32     170 1556.62   174.1 1558.38   178.1 1558.96   190.1 1559.01
#Mann= 5 ,-1,0
       0      .1       0      10     .06       0    84.4    .045       0
    99.3     .06       0     110      .1       0
Bank Sta=84.4,99.3
XS Rating Curve= 0 ,0
Exp/Cntr(USF)=0,0
Exp/Cntr=0.3,0.1

Type RM Length L Ch R = 1 ,7481    ,99.9,117.4,132.7
XS GIS Cut Line= 3
2193581.01581703700937.046126832 2193538.9433966700994.383761762
2193521.81657058701074.060734976
#Sta/Elev= 30
       0 1531.37     5.1 1531.44      15 1531.09      25 1531.05    34.9 1530.72
    40.8 1530.71    49.8 1530.49    60.8  1530.6    69.6 1530.83      74 1530.24
    78.1 1528.28    80.71526.895    82.2 1526.13    82.5 1526.06    86.3 1525.62
    90.3 1525.82    95.41526.843    98.5 1527.41   102.6 1527.97   106.7  1529.9
   110.8 1532.35   114.9 1534.67   116.2 1535.32     119 1536.61   123.1 1537.96
   127.2 1539.52     133 1541.34   139.4 1542.98   147.6 1544.56   152.6 1545.69
#Mann= 5 ,-1,0
       0      .1       0      10     .06       0    80.7    .045       0
    95.4     .06       0  131.12      .1       0
Bank Sta=80.7,95.4
XS Rating Curve= 0 ,0
Exp/Cntr(USF)=0,0
Exp/Cntr=0.3,0.1

Type RM Length L Ch R = 1 ,7364    ,143.7,129.4,112.2
XS GIS Cut Line= 3
2193574.44960472700925.498255101 2193511.1190618700926.008985286
2193406.41937391700925.498255101
#Sta/Elev= 30
       0 1530.25    14.3 1529.73    26.3    1530    30.3 1529.84    38.3 1529.88
    50.3 1529.39    54.3  1529.4    61.5 1529.72    66.3  1529.7    73.5 1529.22
    78.3 1528.75    82.3 1528.01    86.3 1526.73    88.71526.322    90.3 1526.05
    94.3 1525.98   101.71526.312   106.3 1526.72   109.7 1526.73   114.3 1526.34
   118.3  1526.2   126.3 1527.09   130.8 1527.35   134.3  1527.4   138.3 1528.14
   142.3 1529.74   146.3 1530.79   149.9 1531.09   158.6 1531.07     168 1530.88
#Mann= 3 ,-1,0
       0      .1       0    88.7    .045       0   101.7      .1       0
Bank Sta=88.7,101.7
XS Rating Curve= 0 ,0
Exp/Cntr(USF)=0,0
Exp/Cntr=0.3,0.1

Type RM Length L Ch R = 1 ,7234    ,234.8,219,201.5
XS GIS Cut Line= 4
2193430.46055213700766.4822017252193421.74127946700795.772788153
2193404.88718336700847.8672670062193382.98248636700917.218908077
#Sta/Elev= 30
       0  1549.3     2.8 1547.27       4 1546.91     7.2 1546.09    11.2 1546.25
    15.3    1546    19.5 1543.93    23.7 1539.62    26.5 1536.24    27.9 1534.29
    29.7 1532.59      32 1530.22    35.6 1527.96    40.4 1525.16    44.7  1523.1
    49.11521.674    53.1    1521    55.2 1520.99    61.5 1521.03    65.7 1521.47
      71 1524.27    74.2 1525.76    78.3 1526.36    82.5 1526.71    90.9  1527.8
    99.3 1528.23   111.9 1529.18   120.2 1529.56   149.6 1530.01     158 1530.29
#Mann= 3 ,-1,0
       0      .1       0    49.1    .045       0    65.7      .1       0
Bank Sta=49.1,65.7
XS Rating Curve= 0 ,0
Exp/Cntr(USF)=0,0
Exp/Cntr=0.3,0.1

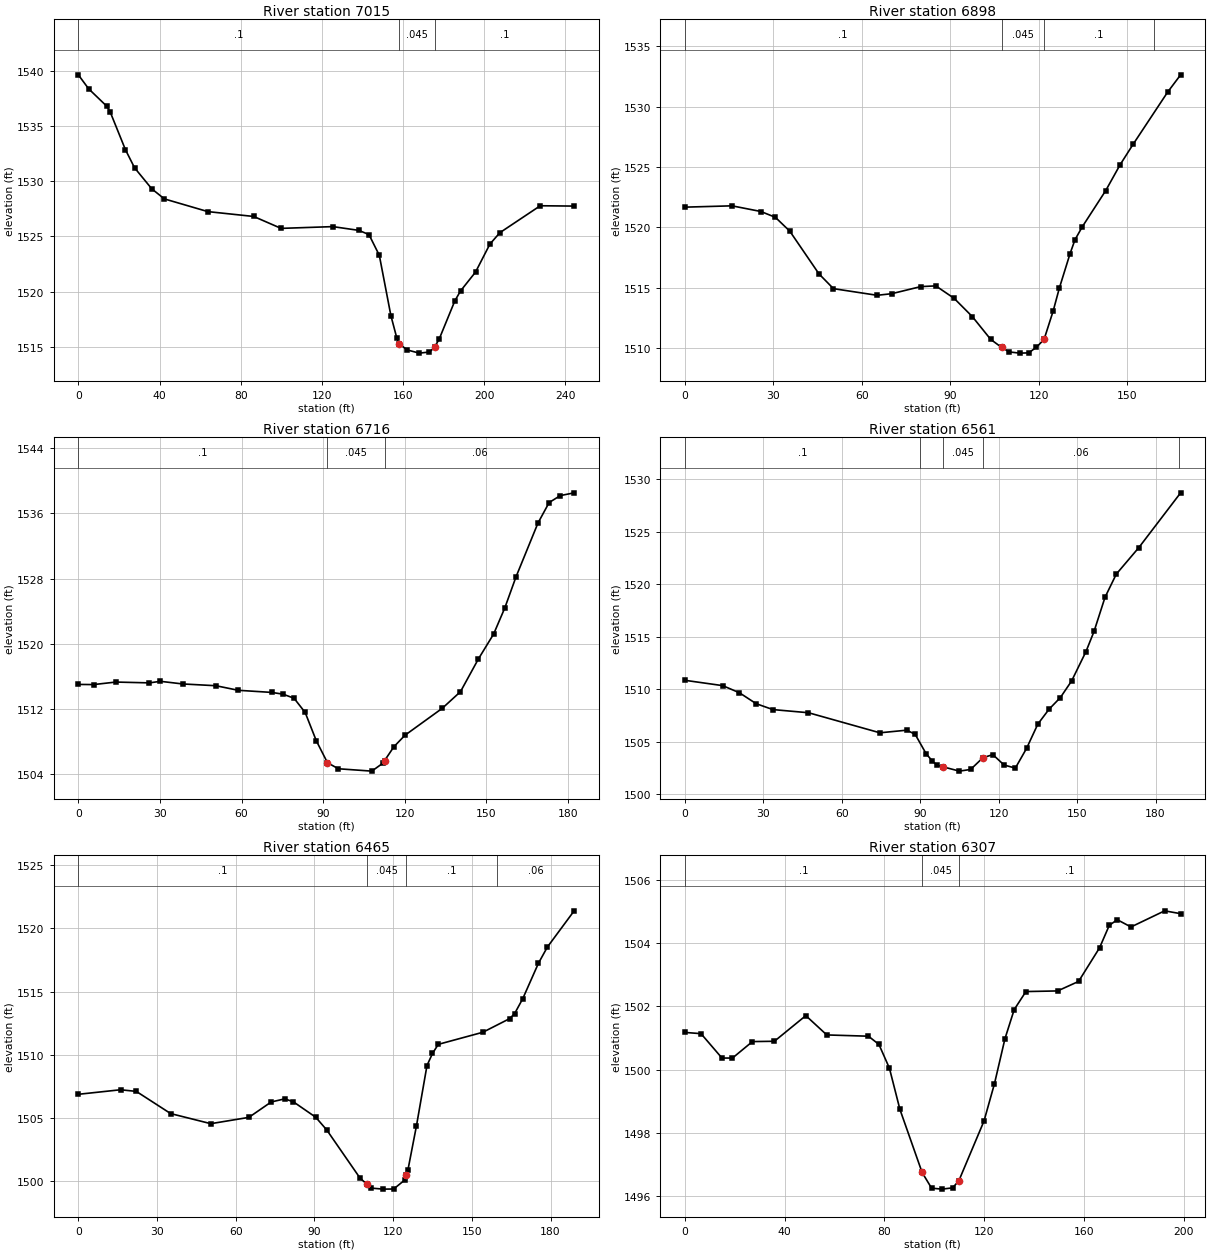
Type RM Length L Ch R = 1 ,7015    ,114.7,117.4,120.1
XS GIS Cut Line= 3
2193143.41267351700780.6642471732193201.12518439700890.981967095
2193297.65318932700961.973462786
#Sta/Elev= 30
       0 1539.63     5.1 1538.36    14.1 1536.77    15.8 1536.22    23.2 1532.85
    27.7 1531.21    36.2  1529.3    42.4 1528.39    63.8 1527.24    86.4  1526.8
    99.9 1525.72   125.4 1525.88   138.2 1525.54   143.2 1525.16   148.3 1523.28
     154 1517.82   156.9  1515.8   158.1 1515.27     162 1514.71     168 1514.42
     173 1514.52   175.5 1514.94   177.9 1515.74   185.5 1519.15   188.3 1520.05
   195.7 1521.76   202.8  1524.3   207.7 1525.33   227.6 1527.77   244.3 1527.74
#Mann= 3 ,-1,0
       0      .1       0   158.1    .045       0   175.5      .1       0
Bank Sta=158.1,175.5
XS Rating Curve= 0 ,0
Exp/Cntr(USF)=0,0
Exp/Cntr=0.3,0.1

Type RM Length L Ch R = 1 ,6898    ,174.3,181.3,186.7
XS GIS Cut Line= 3
2193106.25807424 700924.197380712193152.28684398700988.511552132
2193209.66517339701056.608910109
#Sta/Elev= 30
       0 1521.68      16 1521.79    25.8 1521.32    30.7 1520.84    35.6 1519.69
    45.5 1516.15    50.4 1514.93    65.2 1514.38    70.1 1514.51      80  1515.1
    85.1 1515.16    91.3 1514.13    97.5 1512.61   103.7 1510.73   107.41510.064
     110 1509.69   113.5 1509.59   116.6 1509.61   119.2 1510.08   121.8 1510.72
   124.9 1513.09     127 1514.99   130.6 1517.82   132.3 1518.99   134.8 1520.07
   142.7 1523.05   147.6  1525.2     152 1526.89   163.7 1531.21   168.1 1532.64
#Mann= 4 ,-1,0
       0      .1       0   107.4    .045       0   121.8      .1       0
  159.09     .06       0
Bank Sta=107.4,121.8
XS Rating Curve= 0 ,0
Exp/Cntr(USF)=0,0
Exp/Cntr=0.3,0.1

Type RM Length L Ch R = 1 ,6716    ,155,155.4,152.8
XS GIS Cut Line= 3
2192985.82663559700955.7239353292193004.11203727701038.954039523
2193023.02797004701134.164234472
#Sta/Elev= 30
       0 1515.03     5.6 1515.01    13.8 1515.32    26.1 1515.22    30.2 1515.41
    38.3 1515.09    50.6 1514.87    58.8 1514.31    71.1 1514.05    75.2 1513.84
    79.3 1513.34    83.4 1511.59    87.5 1508.12    91.6 1505.43    95.6 1504.69
   107.9  1504.4     112 1505.38   112.61505.689     116 1507.38   120.1  1508.8
   133.8  1512.1   140.5 1514.14   147.1 1518.16   152.7 1521.21   156.8 1524.41
   160.9  1528.2     169 1534.82   173.1 1537.33   177.2 1538.18   182.3 1538.52
#Mann= 3 ,-1,0
       0      .1       0    91.6    .045       0   112.6     .06       0
Bank Sta=91.6,112.6
XS Rating Curve= 0 ,0
Exp/Cntr(USF)=0,0
Exp/Cntr=0.3,0.1

Type RM Length L Ch R = 1 ,6561    ,96.2,96.5,96.5
XS GIS Cut Line= 3
2192826.30226922700968.9650882692192855.30669947701063.544752126
2192888.09431627701148.035918504
#Sta/Elev= 30
       0 1510.85    14.5 1510.34    20.9 1509.66    27.3 1508.62    33.7 1508.06
    47.3 1507.76    74.6 1505.85    84.9  1506.1    88.1  1505.7    92.3 1503.85
    94.5 1503.21    96.5 1502.74    98.9  1502.6     105  1502.2   109.3 1502.36
     1141503.479   117.8 1503.77   122.1 1502.78   126.4 1502.49   130.7 1504.37
     135 1506.68   139.3  1508.1   143.6  1509.2   147.9 1510.78   153.4 1513.58
   156.5 1515.51   160.7 1518.76     165 1520.96   173.6 1523.48   189.6  1528.7
#Mann= 5 ,-1,0
       0      .1       0      90     .06       0    98.9    .045       0
     114     .06       0  188.93      .1       0
Bank Sta=98.9,114
XS Rating Curve= 0 ,0
Exp/Cntr(USF)=0,0
Exp/Cntr=0.3,0.1

Type RM Length L Ch R = 1 ,6465    ,157.4,157.9,158.1
XS GIS Cut Line= 3
 2192728.7159302700992.0270921252192762.34425512701085.906165879
2192792.46962954701169.976978197
#Sta/Elev= 30
       0 1506.85    16.1 1507.21    22.1 1507.08    35.2 1505.32    50.5 1504.52
      65 1505.02    73.5 1506.24    78.7 1506.49      82 1506.25    90.5 1505.03
    94.7 1504.02   107.4  1500.2   110.11499.702   111.7 1499.41   116.2 1499.33
   120.2 1499.34   124.4 1500.05     125 1500.43   125.6 1500.81   128.9 1504.36
   132.9 1509.13     135 1510.09   137.2 1510.81   154.2 1511.77   164.4 1512.85
   166.3 1513.25   169.4 1514.43   175.4 1517.25   178.8 1518.53     189  1521.4
#Mann= 4 ,-1,0
       0      .1       0   110.1    .045       0     125      .1       0
  159.72     .06       0
Bank Sta=110.1,125
XS Rating Curve= 0 ,0
Exp/Cntr(USF)=0,0
Exp/Cntr=0.3,0.1

Type RM Length L Ch R = 1 ,6307    ,227.9,222,214.5
XS GIS Cut Line= 3
2192584.39436905701038.9666290022192611.01679295701123.037441319
2192645.34570798701228.125956716
#Sta/Elev= 30
       0 1501.18     6.5 1501.14    14.9 1500.37    19.1 1500.37    27.1 1500.89
    35.9  1500.9    48.5 1501.71    56.9  1501.1    73.6 1501.06    77.8  1500.8
      82 1500.05    86.2 1498.75    95.11496.756    98.9 1496.26   103.1 1496.23
   107.3 1496.27   109.8 1496.49   119.9 1498.38   124.1 1499.56   128.3 1500.98
     132  1501.9   136.7 1502.47   149.4 1502.49   157.8 1502.79   166.2 1503.85
   170.1 1504.56   173.3 1504.74   178.8 1504.51   192.3 1505.02   198.7 1504.93
#Mann= 3 ,-1,0
       0      .1       0    95.1    .045       0   109.8      .1       0
Bank Sta=95.1,109.8
XS Rating Curve= 0 ,0
Exp/Cntr(USF)=0,0
Exp/Cntr=0.3,0.1

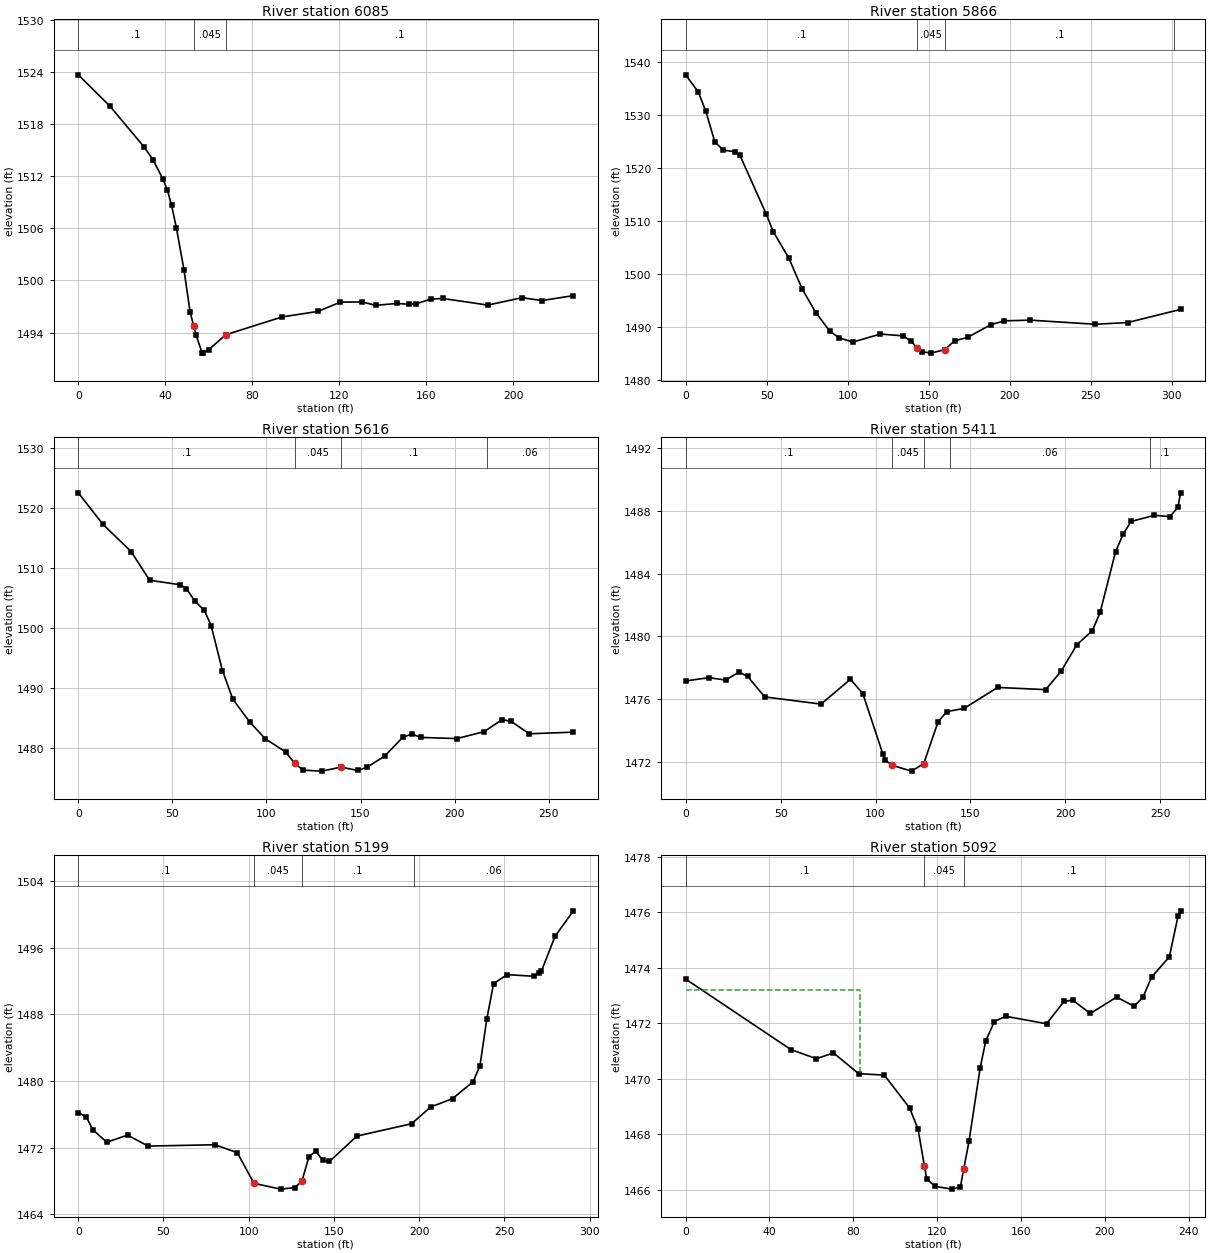
Type RM Length L Ch R = 1 ,6085    ,217.1,219,218.4
XS GIS Cut Line= 4
2192364.86556557701108.0348184222192385.88326865701125.549570988
2192439.82870656701172.4891078652192522.49833867701271.272312338
#Sta/Elev= 30
       0 1523.67    14.5 1520.08    30.4 1515.33    34.4 1513.87      39 1511.64
      41 1510.38    42.9 1508.67    45.1 1506.08    48.6 1501.25    51.4 1496.42
    53.11494.737    54.2  1493.7    56.9  1491.7    57.3 1491.64    59.9 1492.02
    67.91493.761    93.8 1495.81   110.2 1496.44   120.6 1497.51   130.6 1497.53
   136.8 1497.14   146.7 1497.36   151.9 1497.26   155.5 1497.33   162.1 1497.85
   167.6 1497.93   188.4 1497.17   204.1 1498.02   213.2 1497.69   227.7 1498.26
#Mann= 3 ,-1,0
       0      .1       0    53.1    .045       0    67.9      .1       0
Bank Sta=53.1,67.9
XS Rating Curve= 0 ,0
Exp/Cntr(USF)=0,0
Exp/Cntr=0.3,0.1

Type RM Length L Ch R = 1 ,5866    ,244.6,249.9,252.1
XS GIS Cut Line= 4
2192234.14053168701249.8752463172192285.28360918701291.210062373
2192379.16268293701374.5802845882192470.23939628701443.238114647
#Sta/Elev= 30
       0 1537.55     7.8 1534.31    12.3 1530.82      18 1524.92    23.2 1523.35
    30.7 1523.05    33.5 1522.36    49.8 1511.24      54    1508    63.5 1503.09
      72  1497.1    80.3 1492.72      89 1489.19    94.7 1487.95   103.2 1487.16
   120.2 1488.67   134.4 1488.32   139.2 1487.29   142.9 1485.97   145.7 1485.37
   151.4 1485.07   159.9 1485.74   165.9 1487.39     174 1488.05   188.2 1490.42
   196.7 1491.16   212.6 1491.29   252.7 1490.51   272.7 1490.84   305.4 1493.32
#Mann= 4 ,-1,0
       0      .1       0   142.9    .045       0   159.9      .1       0
  301.31     .06       0
Bank Sta=142.9,159.9
XS Rating Curve= 0 ,0
Exp/Cntr(USF)=0,0
Exp/Cntr=0.3,0.1

Type RM Length L Ch R = 1 ,5616    ,205.4,204.6,205.3
XS GIS Cut Line= 3
2192081.00315275701358.1384555872192113.93088758701405.077992464
2192227.42648421701576.722567612
#Sta/Elev= 30
       0 1522.49    13.1 1517.23    28.1 1512.69    37.9 1507.91    54.3 1507.15
    57.5 1506.51    61.9 1504.45      67 1502.88    70.6 1500.35    76.6 1492.85
    82.1  1488.1      91  1484.3    99.4 1481.47   110.2 1479.27     115 1477.36
   119.6 1476.23   129.4 1476.07   139.61476.733   148.5 1476.19   153.4  1476.7
   162.9 1478.59   172.5 1481.73   177.3 1482.25   182.1 1481.69   201.3  1481.5
   215.7 1482.66   225.3 1484.67   230.1 1484.35   239.7  1482.3   263.1 1482.57
#Mann= 4 ,-1,0
       0      .1       0     115    .045       0   139.6      .1       0
  217.34     .06       0
Bank Sta=115,139.6
XS Rating Curve= 0 ,0
Exp/Cntr(USF)=0,0
Exp/Cntr=0.3,0.1

Type RM Length L Ch R = 1 ,5411    ,208.9,212.2,215.2
XS GIS Cut Line= 4
2191968.67473646701516.3450505242192010.10062923701595.224490181
2192047.55417612701660.4844582422192067.98338351701754.685803444
#Sta/Elev= 30
       0 1477.17    12.1 1477.38      21 1477.23    28.1 1477.73    32.6 1477.47
    41.6 1476.16    71.3  1475.7    86.8 1477.28    93.3 1476.37   103.8 1472.55
   105.2 1472.14   108.61471.816     119 1471.44   125.4 1471.92   132.9 1474.56
   137.5 1475.22   146.7 1475.43   164.3 1476.76   189.6 1476.62   197.8  1477.8
     206 1479.47   214.2 1480.37   218.3 1481.53   226.4 1485.38   230.5 1486.53
   234.6 1487.31   246.9  1487.7   255.1 1487.62   259.2 1488.21   260.7 1489.13
#Mann= 5 ,-1,0
       0      .1       0   108.6    .045       0   125.4      .1       0
   139.1     .06       0  244.34      .1       0
Bank Sta=108.6,125.4
XS Rating Curve= 0 ,0
Exp/Cntr(USF)=0,0
Exp/Cntr=0.3,0.1

Type RM Length L Ch R = 1 ,5199    ,97.4,106.6,111.7
XS GIS Cut Line= 4
2191796.70555456701540.6749879222191809.16048972701618.518332661
2191823.95072522701674.5655408722191834.84879349701827.916930007
#Sta/Elev= 30
       0  1476.2     4.6 1475.73     8.6 1474.14    16.7 1472.67    28.9 1473.51
      41  1472.2    80.2 1472.36    93.3 1471.41   103.1 1467.73   118.8 1467.04
   127.1 1467.23   131.2 1467.99   135.4 1470.95   139.4  1471.6   143.4 1470.48
   147.4 1470.36   163.5  1473.4   195.6 1474.88   206.8 1476.89   219.6 1477.88
   231.7 1479.92   235.7 1481.81   239.7 1487.39   243.7 1491.68   251.7 1492.75
   267.7 1492.55   270.5 1492.93   271.8 1493.19   279.8 1497.35   290.5  1500.4
#Mann= 4 ,-1,0
       0      .1       0   103.1    .045       0   131.2      .1       0
   196.8     .06       0
Bank Sta=103.1,131.2
XS Rating Curve= 0 ,0
Exp/Cntr(USF)=0,0
Exp/Cntr=0.3,0.1

Type RM Length L Ch R = 1 ,5092    ,151.9,147.6,144.9
XS GIS Cut Line= 4
  2191736.312723701535.8689361642191723.70210116701602.424995916
2191711.79206941701686.4958082342191687.27141582701766.363079936
#Sta/Elev= 30
       0 1473.59    50.2 1471.05    62.4 1470.72    70.5 1470.93    82.6 1470.18
    94.8 1470.13   106.9 1468.94   110.9 1468.18   113.9 1466.87     115 1466.39
     119 1466.12   127.1 1466.02   131.1  1466.1   132.7 1466.75   135.2 1467.74
   140.5 1470.38   143.2 1471.36   147.3 1472.06   152.7 1472.25   172.2 1471.98
   180.6 1472.79   184.7 1472.83   193.1 1472.35   205.6 1472.94     214 1472.61
   218.2 1472.94   222.4 1473.67   230.8 1474.39     235 1475.88   236.2 1476.05
#Mann= 3 ,-1,0
       0      .1       0   113.9    .045       0   132.7      .1       0
#XS Ineff= 2 , 0
        83.15353 1473.19
Permanent Ineff=
       T       F
Bank Sta=113.9,132.7
XS Rating Curve= 0 ,0
Exp/Cntr(USF)=0,0
Exp/Cntr=0.3,0.1