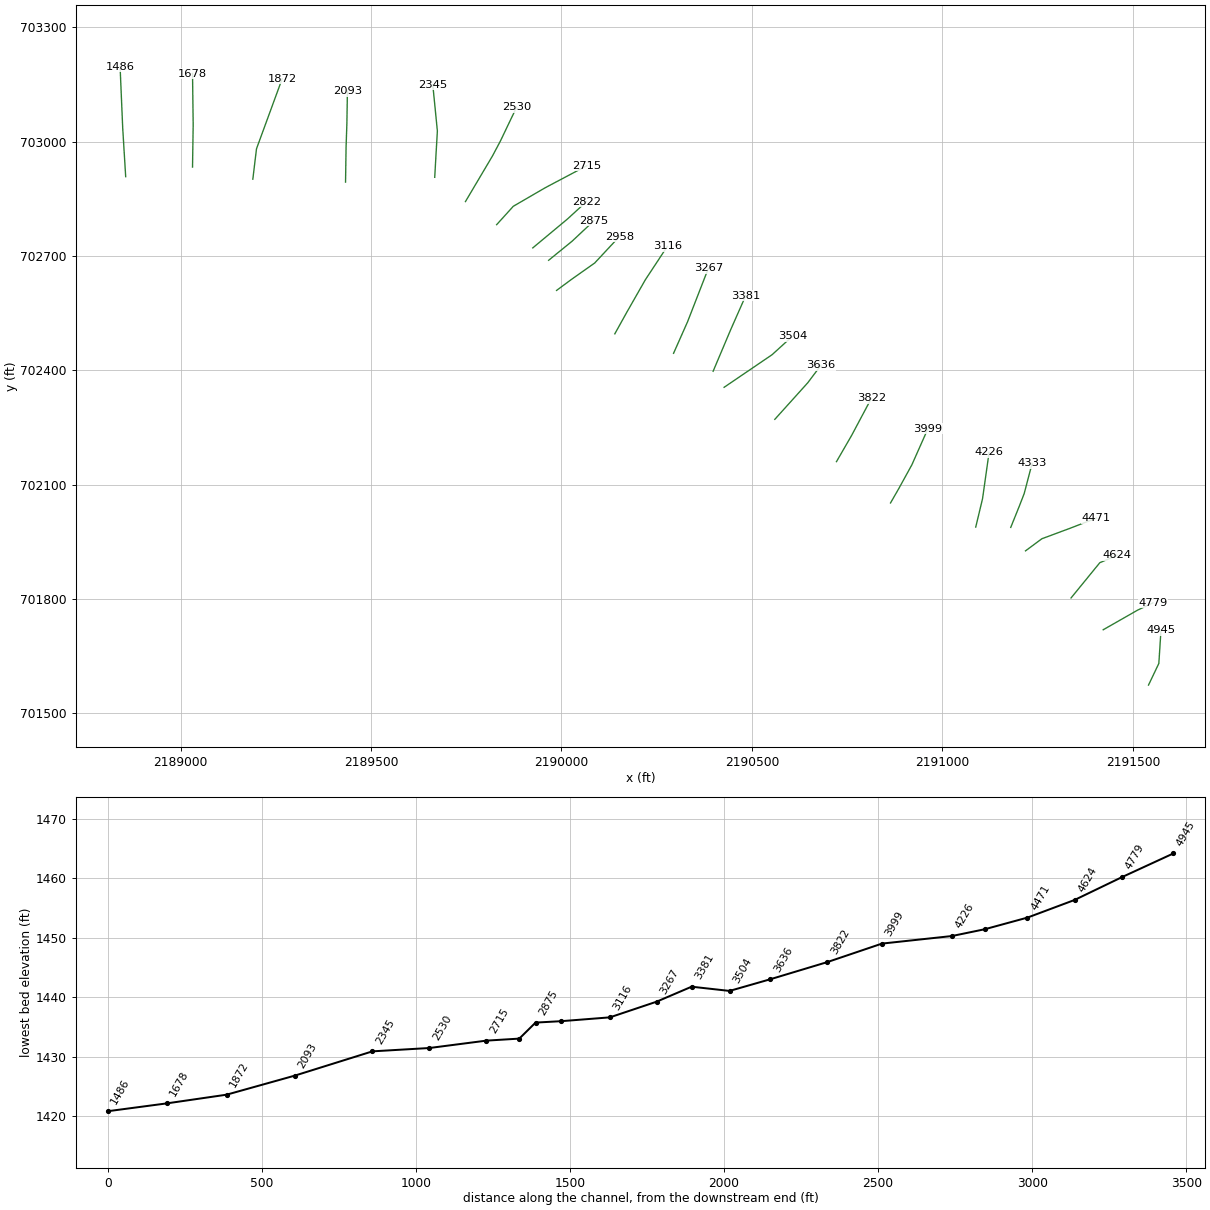
HEC-RAS study TRUBIERN.prj: TRUBIERN

--- TRUBIERN.g01 (geometry) --- (continued)

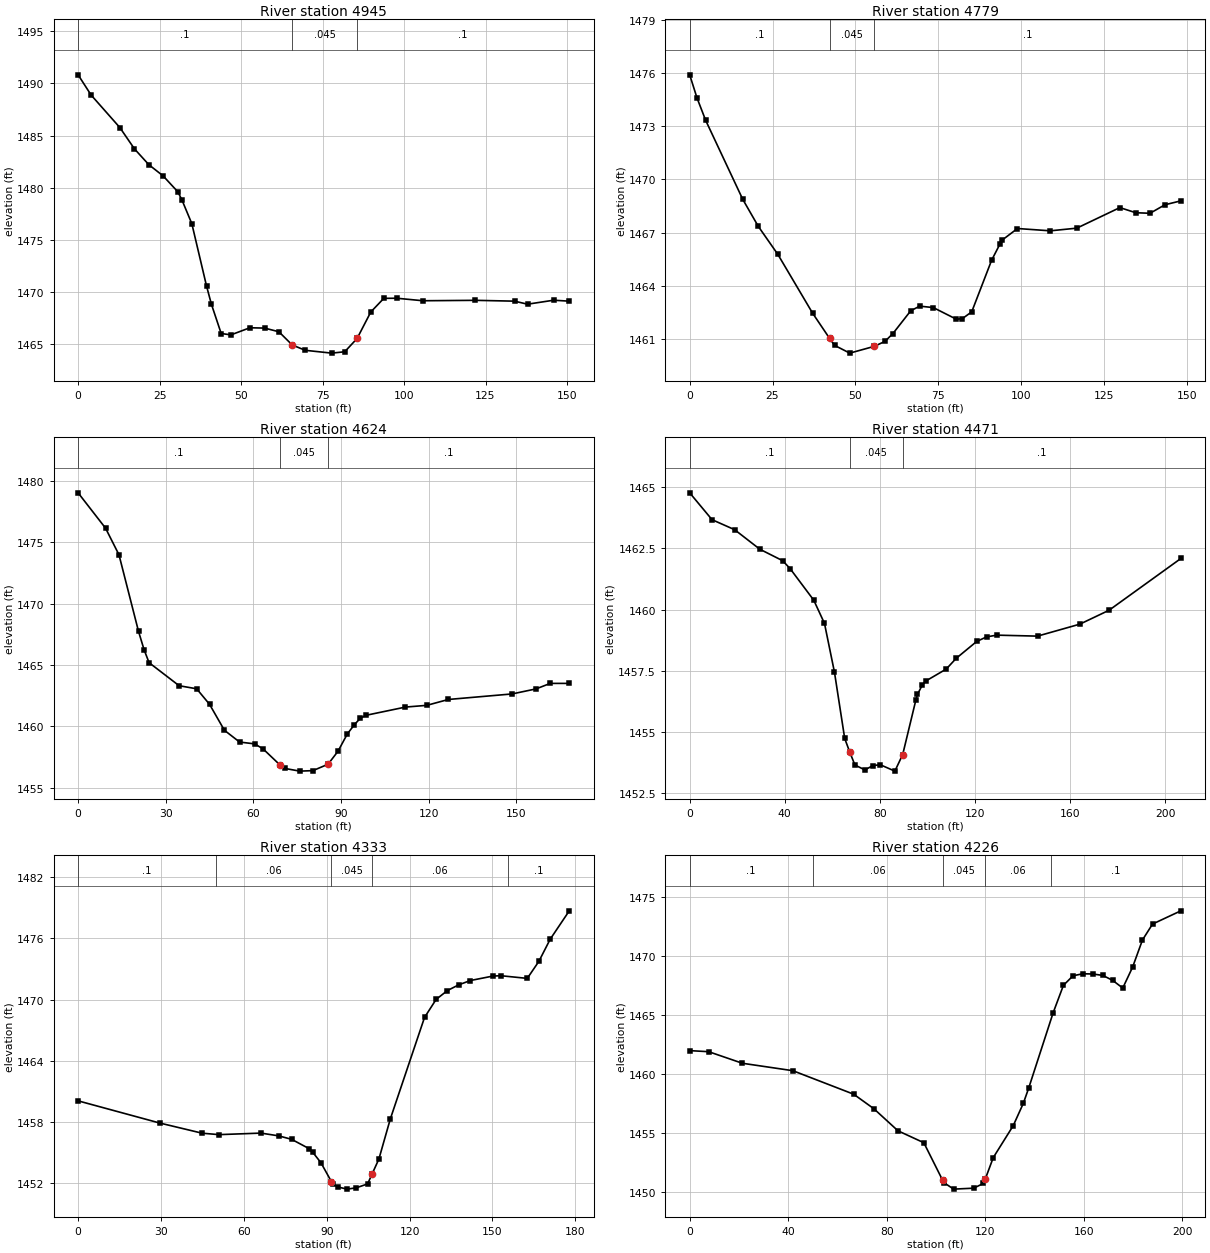
Type RM Length L Ch R = 1 ,4945    ,177.9,166,152
XS GIS Cut Line= 3
2191541.20194526701573.6021280422191568.31478224701630.349926356
2191573.98956207701717.993748197
#Sta/Elev= 30
       0 1490.83       4 1488.89    12.8 1485.78    17.3 1483.73    21.7 1482.22
    26.1 1481.14    30.6 1479.62    31.9 1478.81    34.9 1476.56    39.4  1470.6
    40.9 1468.85    43.9 1466.04    46.9 1465.91    52.7 1466.59    57.2 1466.56
    61.6 1466.21    65.7 1464.94    69.7 1464.43    77.8 1464.16    81.8 1464.29
    85.61465.563    89.8  1468.1    93.8 1469.41    97.8 1469.42   105.8 1469.18
   121.9 1469.22   133.9 1469.14   137.9 1468.85   145.9 1469.23   150.7 1469.14
#Mann= 3 ,-1,0
       0      .1       0    65.7    .045       0    85.6      .1       0
Bank Sta=65.7,85.6
XS Rating Curve= 0 ,0
Exp/Cntr(USF)=0,0
Exp/Cntr=0.3,0.1

Type RM Length L Ch R = 1 ,4779    ,148.8,154.8,158.7
XS GIS Cut Line= 3
2191422.24314701701718.8059656562191512.64238973701770.389714324
2191552.47934415701789.286731162
#Sta/Elev= 30
       0  1475.9     2.2  1474.6     4.8 1473.34      16 1468.88    20.7 1467.35
    26.6 1465.77    37.1 1462.45    42.21461.035    43.7 1460.64    48.3  1460.2
    55.71460.583    58.9 1460.86    61.3  1461.3    66.7 1462.59    69.4 1462.85
    73.5 1462.77    80.5 1462.11    82.3 1462.15    85.1 1462.53    91.1 1465.44
    93.6 1466.35    94.3 1466.58    98.9 1467.23   108.8  1467.1   116.8 1467.25
   129.8 1468.41   134.6 1468.12   138.9 1468.09   143.4 1468.57   148.2 1468.79
#Mann= 3 ,-1,0
       0      .1       0    42.2    .045       0    55.7      .1       0
Bank Sta=42.2,55.7
XS Rating Curve= 0 ,0
Exp/Cntr(USF)=0,0
Exp/Cntr=0.3,0.1

Type RM Length L Ch R = 1 ,4624    ,158.4,152.8,141.6
XS GIS Cut Line= 3
2191337.85917092701802.3387247752191413.33374268701894.837636027
2191458.16450335701914.131887454
#Sta/Elev= 30
       0 1479.02     9.4 1476.14      14 1473.97    20.7 1467.72    22.6 1466.23
    24.3 1465.18    34.6  1463.3    40.6 1463.05      45 1461.79    50.1 1459.67
    55.3 1458.71    60.5 1458.56    63.4 1458.14    69.1 1456.85    70.8 1456.56
    75.9 1456.34    80.4 1456.38    85.61456.902      89 1457.96    92.2 1459.37
    94.6 1460.12    96.6 1460.64    98.6 1460.89   112.1 1461.56   119.4  1461.7
   126.8 1462.18   148.6 1462.63   156.8 1463.04   161.7 1463.49   168.2 1463.49
#Mann= 3 ,-1,0
       0      .1       0    69.1    .045       0    85.6      .1       0
Bank Sta=69.1,85.6
XS Rating Curve= 0 ,0
Exp/Cntr(USF)=0,0
Exp/Cntr=0.3,0.1

Type RM Length L Ch R = 1 ,4471    ,127.3,138,151
XS GIS Cut Line= 4
2191218.22700782701925.9178630432191261.25091859701957.772104671
2191333.64692229701984.6620489032191404.38816019702011.965684584
#Sta/Elev= 30
       0 1464.78     9.4 1463.68    18.9 1463.27    29.5 1462.47    39.1    1462
    42.2 1461.68    52.2 1460.38    56.7 1459.43    60.9 1457.43    65.2 1454.72
    67.31454.167    69.5 1453.63    73.7 1453.43    77.1 1453.61    80.2 1453.64
    86.3 1453.38    89.6 1454.06    95.1 1456.28    95.8 1456.52    97.8  1456.9
    99.3 1457.07   107.9 1457.56   112.1    1458   120.7 1458.69   124.9 1458.88
   129.2 1458.95   146.3 1458.91   164.1  1459.4   176.4 1459.97   206.6 1462.09
#Mann= 3 ,-1,0
       0      .1       0    67.3    .045       0    89.6      .1       0
Bank Sta=67.3,89.6
XS Rating Curve= 0 ,0
Exp/Cntr(USF)=0,0
Exp/Cntr=0.3,0.1

Type RM Length L Ch R = 1 ,4333    ,104.7,107.3,108.6
XS GIS Cut Line= 4
2191179.51750605701987.4761091682191202.84715647702045.484969667
2191214.82724722702076.3809931942191235.63477327702155.827910834
#Sta/Elev= 30
       0 1460.08    29.5 1457.91    44.9 1456.91      51 1456.77    66.2 1456.92
    72.6 1456.65    77.3 1456.31    83.6  1455.4      85 1455.02    87.9 1454.02
    91.71452.164    92.2  1451.9    94.2 1451.63    97.4 1451.43   100.7 1451.56
   104.8 1451.94   106.41452.896   108.9 1454.39     113 1458.29   125.4 1468.25
   129.6 1470.02   133.7 1470.89   137.8 1471.45     142 1471.87   150.2 1472.31
   153.1 1472.34   162.6 1472.08   166.8 1473.75   170.9 1475.92   177.8  1478.7
#Mann= 5 ,-1,0
       0      .1       0      50     .06       0    91.7    .045       0
   106.4     .06       0  155.66      .1       0
Bank Sta=91.7,106.4
XS Rating Curve= 0 ,0
Exp/Cntr(USF)=0,0
Exp/Cntr=0.3,0.1

Type RM Length L Ch R = 1 ,4226    ,230.2,227,217.5
XS GIS Cut Line= 3
2191087.61132862701988.4007151182191105.51529791702063.130326067
2191122.64083375 702184.56594386
#Sta/Elev= 30
       0 1462.01     7.7 1461.92    21.4 1460.94    41.9 1460.31    66.6 1458.32
    74.8 1457.09    84.6 1455.22    95.1 1454.21   102.71451.046   103.2 1450.84
   107.2 1450.28   115.3 1450.36   119.3 1450.76     120  1451.1   123.3 1452.95
   131.4 1455.65   135.5 1457.54   137.7 1458.84   147.6  1465.2   151.8 1467.54
   155.7 1468.35   159.7 1468.52   163.7  1468.5   167.8 1468.38   171.8 1467.96
   175.9 1467.31   179.9 1469.08   183.9 1471.38     188 1472.73   199.5 1473.85
#Mann= 5 ,-1,0
       0      .1       0      50     .06       0   102.7    .045       0
     120     .06       0  146.84      .1       0
Bank Sta=102.7,120
XS Rating Curve= 0 ,0
Exp/Cntr(USF)=0,0
Exp/Cntr=0.3,0.1

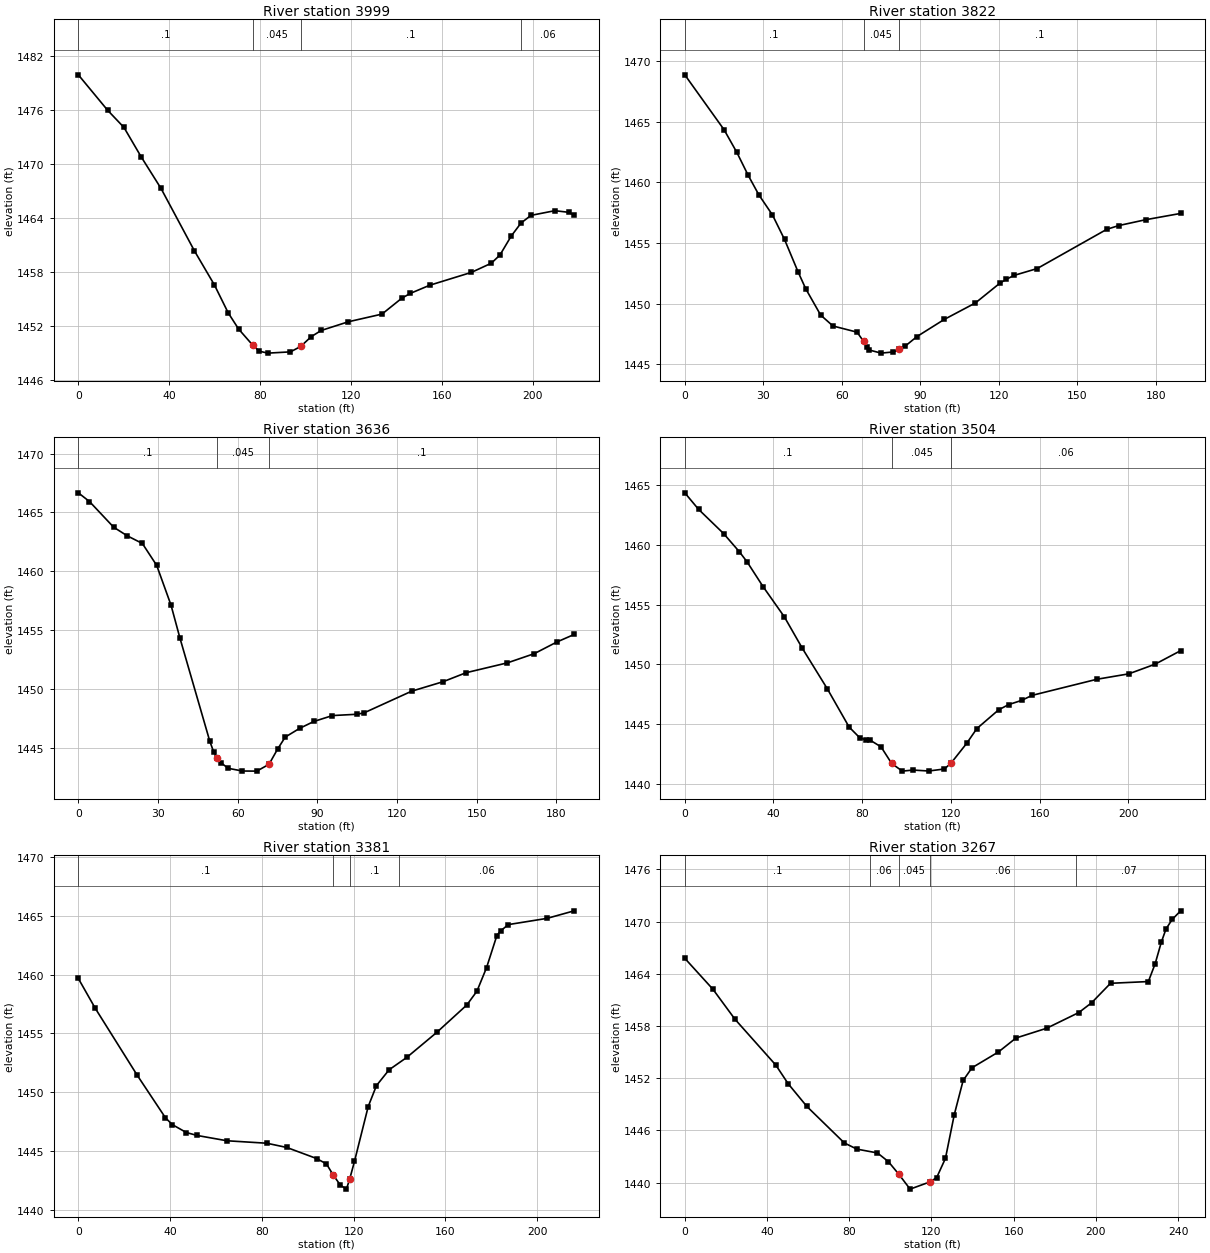
Type RM Length L Ch R = 1 ,3999    ,177.2,176.9,176.5
XS GIS Cut Line= 4
2190863.92991906702051.7577230662190885.64821224702089.589588609
2190919.97712727702151.9421077452190962.01253343702246.521771602
#Sta/Elev= 30
       0 1479.88    12.9 1475.95    20.1 1474.04    27.6 1470.81    36.4 1467.28
    51.1 1460.36    59.9 1456.58      66 1453.47    70.6 1451.67    76.91449.859
    79.7 1449.22    83.5 1449.01    93.4 1449.15    97.9 1449.75   102.5 1450.83
   106.9 1451.52   118.9 1452.49   133.7 1453.34   142.4  1455.1   146.2 1455.64
   154.7 1456.54   173.1 1457.97   181.8 1458.98   185.6 1459.88   190.6    1462
   194.9 1463.44   199.3 1464.29   209.8 1464.81   215.9 1464.63   218.3 1464.31
#Mann= 4 ,-1,0
       0      .1       0    76.9    .045       0    97.9      .1       0
   194.8     .06       0
Bank Sta=76.9,97.9
XS Rating Curve= 0 ,0
Exp/Cntr(USF)=0,0
Exp/Cntr=0.3,0.1

Type RM Length L Ch R = 1 ,3822    ,188.5,185.5,181.9
XS GIS Cut Line= 3
2190721.99036426702160.2090709562190761.71382308702228.936960025
2190813.41737266702326.038748252
#Sta/Elev= 30
       0 1468.88      15 1464.35    19.9 1462.47    24.2 1460.59    28.3 1458.97
    33.5 1457.31    38.1 1455.29    43.3  1452.6    46.2 1451.22    51.9 1449.05
    56.6 1448.15    65.8 1447.64    68.3 1446.88    69.6 1446.38    70.4 1446.17
      75 1445.91    79.7 1446.01    81.91446.211    84.2 1446.49    88.7 1447.28
    99.1 1448.69     111 1450.05   120.4 1451.69   122.8    1452   125.7 1452.32
   134.6 1452.89   161.2 1456.13   165.8 1456.44     176 1456.92   189.4 1457.44
#Mann= 3 ,-1,0
       0      .1       0    68.3    .045       0    81.9      .1       0
Bank Sta=68.3,81.9
XS Rating Curve= 0 ,0
Exp/Cntr(USF)=0,0
Exp/Cntr=0.3,0.1

Type RM Length L Ch R = 1 ,3636    ,135.7,132.1,127.6
XS GIS Cut Line= 3
2190560.12464306702271.2906589722190646.50740272702367.131385014
 2190681.1866128702413.160154758
#Sta/Elev= 30
       0 1466.66     4.2 1465.92    13.3 1463.74    18.4 1463.01    24.1 1462.36
    29.5  1460.5    34.9 1457.12    38.2 1454.37    49.5 1445.56      51 1444.63
    52.4 1444.13    53.8 1443.72    56.4 1443.26    61.8 1443.03    67.2 1443.02
    71.8  1443.6      75 1444.88    77.9 1445.91    83.3 1446.65    88.7 1447.24
    95.7 1447.74   104.9 1447.85   107.6 1447.97   125.5 1449.81   137.4 1450.62
     146 1451.38   161.6 1452.22   171.7    1453   180.2 1453.99   186.7 1454.63
#Mann= 3 ,-1,0
       0      .1       0    52.4    .045       0    71.8      .1       0
Bank Sta=52.4,71.8
XS Rating Curve= 0 ,0
Exp/Cntr(USF)=0,0
Exp/Cntr=0.3,0.1

Type RM Length L Ch R = 1 ,3504    ,117.7,123.2,128
XS GIS Cut Line= 3
 2190427.0094471702355.369839381 2190552.9042392702440.901415699
2190605.76083131702488.952863069
#Sta/Elev= 30
       0 1464.35     6.2 1462.97    17.5 1460.94    24.6 1459.42    28.1 1458.57
    35.3  1456.5    44.9 1453.97      53 1451.34    64.3 1447.94    74.1 1444.75
    78.8 1443.87    81.5 1443.68    83.6 1443.65    88.5 1443.09    93.3  1441.7
    98.1 1441.06   102.9 1441.15     110 1441.07   117.1 1441.24   120.2 1441.76
   127.1 1443.38   131.7 1444.62   141.6  1446.2   146.1 1446.63   151.9 1446.98
   156.6  1447.4   185.9 1448.75   200.2  1449.2   212.1 1450.01   223.6 1451.14
#Mann= 3 ,-1,0
       0      .1       0    93.3    .045       0   120.2     .06       0
Bank Sta=93.3,120.2
XS Rating Curve= 0 ,0
Exp/Cntr(USF)=0,0
Exp/Cntr=0.3,0.1

Type RM Length L Ch R = 1 ,3381    ,113.3,113.7,114
XS GIS Cut Line= 3
2190398.14475163702397.4712610892190444.85075847702508.008810618
2190483.77243084702595.971790172
#Sta/Elev= 30
       0 1459.67     7.4 1457.13    25.7 1451.44      38 1447.83      41 1447.25
    47.1 1446.58    51.8 1446.33    64.8 1445.88    82.2 1445.67    90.9 1445.31
   103.9 1444.37   108.2 1443.91   111.2 1442.95   114.3  1442.1   116.9 1441.77
   118.3 1442.61   120.4 1444.12   126.4 1448.79     130 1450.57   135.5 1451.91
   143.2 1452.96   156.3 1455.09   169.4 1457.42   173.8 1458.59     178 1460.59
   182.5 1463.32   184.1 1463.71   187.5 1464.25   204.4 1464.78   216.2 1465.42
#Mann= 4 ,-1,0
       0      .1       0   111.2    .045       0   118.3      .1       0
     140     .06       0
Bank Sta=111.2,118.3
XS Rating Curve= 0 ,0
Exp/Cntr(USF)=0,0
Exp/Cntr=0.3,0.1

Type RM Length L Ch R = 1 ,3267    ,153.6,151.5,149.3
XS GIS Cut Line= 3
2190294.27036753702444.6487420062190331.04294084702527.387031949
2190385.69107061702667.837832777
#Sta/Elev= 30
       0 1465.78    13.7 1462.22    24.4 1458.78    44.3  1453.5    50.3 1451.36
    59.4 1448.75    77.6 1444.56    83.7 1443.85    93.7 1443.41      99 1442.42
   104.11440.964   109.6 1439.25   119.11440.068   122.5 1440.56   126.8 1442.79
   131.1 1447.82   135.4 1451.74   139.7  1453.2   152.6 1455.02   161.1 1456.62
     176 1457.74   191.7 1459.55   197.9 1460.67   207.1 1462.91   225.5 1463.11
   228.8 1465.15   231.8 1467.63   234.1 1469.16   237.1 1470.25   241.2 1471.24
#Mann= 5 ,-1,0
       0      .1       0      90     .06       0   104.1    .045       0
   119.1     .06       0  190.54     .07       0
Bank Sta=104.1,119.1
XS Rating Curve= 0 ,0
Exp/Cntr(USF)=0,0
Exp/Cntr=0.3,0.1

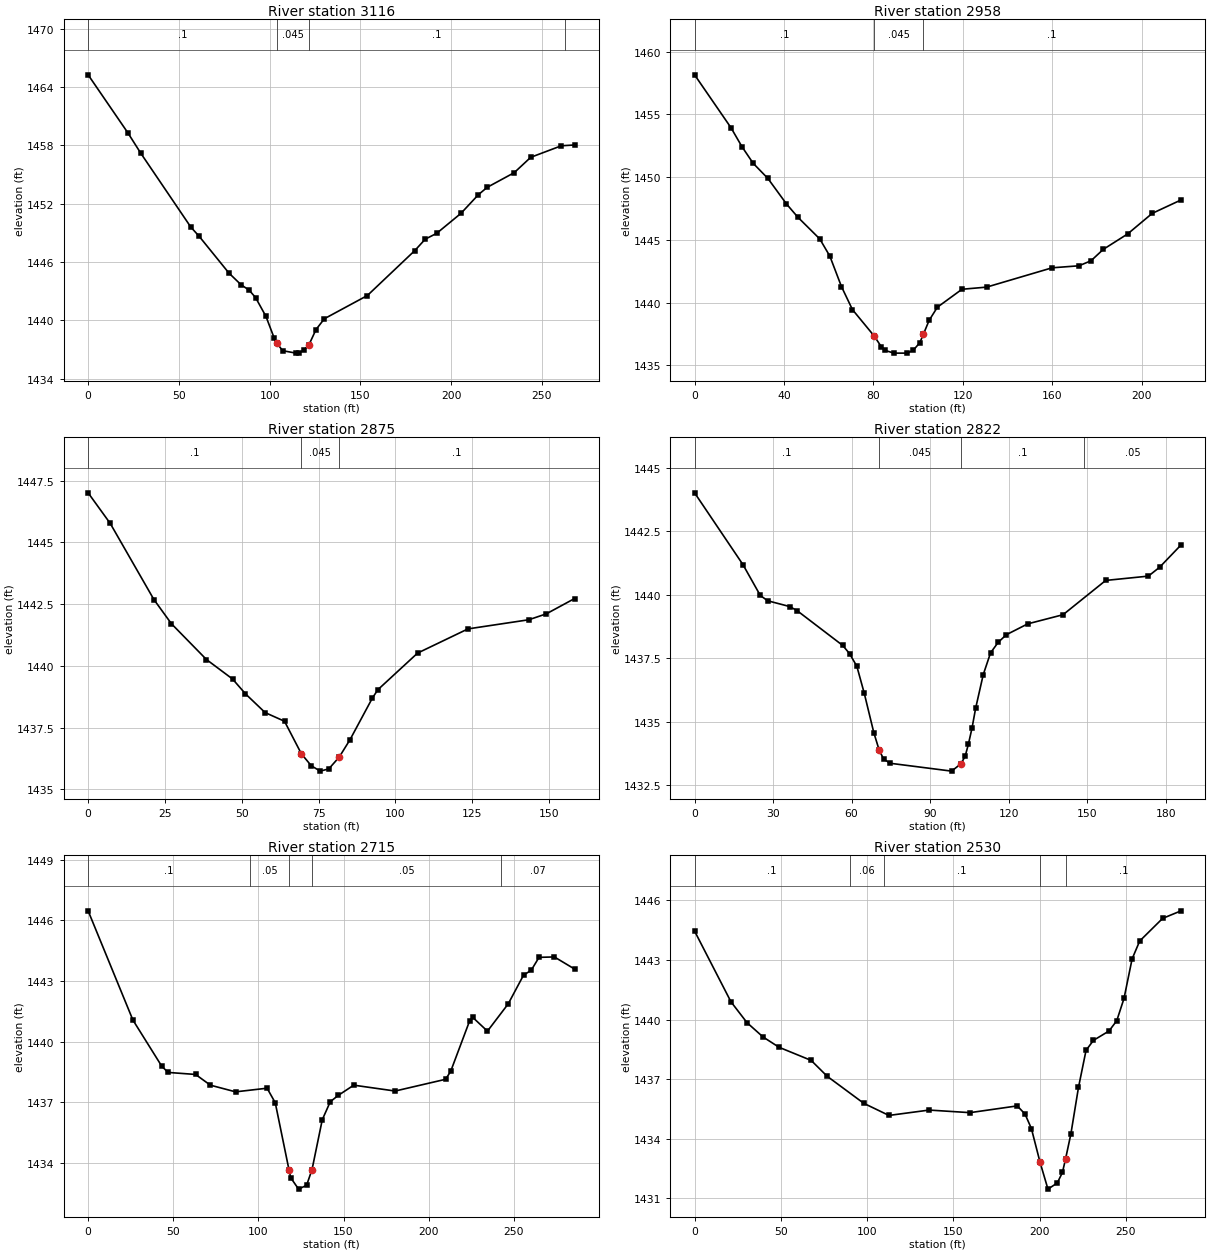
Type RM Length L Ch R = 1 ,3116    ,165.2,157.3,151.4
XS GIS Cut Line= 4
2190140.02985171702495.721760489 2190170.6736628702550.880620451
2190220.21449073702637.7047518722190277.99330684702725.385834727
#Sta/Elev= 30
       0 1465.26    21.8 1459.32    29.1 1457.17    56.6 1449.59    61.2 1448.64
    77.6 1444.86    84.2 1443.67    88.8 1443.09    92.3 1442.33      98  1440.4
   102.6 1438.14     104 1437.65   107.2 1436.87   114.6 1436.62   116.4 1436.65
   118.7 1436.91   121.6 1437.44   125.6 1439.05   130.2 1440.16   153.9 1442.55
     180 1447.17   185.8 1448.35   192.1 1448.95   205.5 1451.01   215.1 1452.93
   219.9 1453.68   234.8 1455.19   243.9 1456.77   260.8 1457.96   268.1 1458.04
#Mann= 4 ,-1,0
       0      .1       0     104    .045       0   121.6      .1       0
  263.06     .06       0
Bank Sta=104,121.6
XS Rating Curve= 0 ,0
Exp/Cntr(USF)=0,0
Exp/Cntr=0.3,0.1

Type RM Length L Ch R = 1 ,2958    ,84.7,83.9,85
XS GIS Cut Line= 4
2189987.11161692702609.6794599522190026.43784116702638.791080487
2190087.21473315702681.6924160132190151.56673644702750.640990965
#Sta/Elev= 30
       0 1458.16    16.3 1453.94    21.2 1452.43    26.2 1451.11    32.8  1449.9
    41.1 1447.87    46.2 1446.81      56 1445.08    60.5 1443.71    65.7 1441.28
    70.6 1439.45    80.4 1437.33    83.5 1436.49    85.3 1436.19    89.2 1435.98
    95.1 1435.98    97.8 1436.21   100.7  1436.8   102.31437.466   104.9 1438.59
   108.6 1439.64   119.6 1441.07   130.6 1441.24   159.9 1442.78   171.9 1442.94
   177.3 1443.34   182.8 1444.25   193.7 1445.48   204.7 1447.12   217.6 1448.19
#Mann= 3 ,-1,0
       0      .1       0    80.4    .045       0   102.3      .1       0
Bank Sta=80.4,102.3
XS Rating Curve= 0 ,0
Exp/Cntr(USF)=0,0
Exp/Cntr=0.3,0.1

Type RM Length L Ch R = 1 ,2875    ,53.4,52.7,53.2
XS GIS Cut Line= 3
2189966.34402777702688.839196972 2190027.8665654702738.901654068
2190085.46854917702792.884665033
#Sta/Elev= 22
       0 1447.01     7.2 1445.77    21.4 1442.69    27.1 1441.71    38.5 1440.26
      47 1439.47    51.2 1438.87    57.6 1438.11    63.9 1437.76    69.4 1436.44
    72.6 1435.96    75.5 1435.74    78.3 1435.83    81.71436.308    85.2 1437.01
    92.5  1438.7    94.3 1439.04   107.2 1440.52   123.6  1441.5   143.4 1441.87
   149.1 1442.11   158.3 1442.73
#Mann= 3 ,-1,0
       0      .1       0    69.4    .045       0    81.7      .1       0
Bank Sta=69.4,81.7
XS Rating Curve= 0 ,0
Exp/Cntr(USF)=0,0
Exp/Cntr=0.3,0.1

Type RM Length L Ch R = 1 ,2822    ,109.6,107,105
XS GIS Cut Line= 3
2189924.67743864702721.3689967382190015.89640331702797.322746905
2190065.41526984702842.746068084
#Sta/Elev= 30
       0 1444.01    18.5 1441.18    25.1 1439.97    27.9 1439.76    36.4 1439.53
    39.3 1439.36    56.6    1438    59.2 1437.68      62 1437.18    64.8 1436.13
    68.5 1434.56    70.5 1433.89    72.2 1433.53    74.7 1433.36    98.2 1433.05
   101.8 1433.34   103.4 1433.64   104.6  1434.1     106 1434.74   107.4 1435.53
   110.3 1436.85   113.1 1437.71     116 1438.12   119.1 1438.42   127.3 1438.85
   140.8 1439.21   157.1 1440.56   173.4 1440.73   177.7 1441.08   185.9 1441.96
#Mann= 4 ,-1,0
       0      .1       0    70.5    .045       0   101.8      .1       0
   148.7     .05       0
Bank Sta=70.5,101.8
XS Rating Curve= 0 ,0
Exp/Cntr(USF)=0,0
Exp/Cntr=0.3,0.1

Type RM Length L Ch R = 1 ,2715    ,177.2,184.9,192.2
XS GIS Cut Line= 4
 2189829.8442584702782.358865866 2189873.5400631702830.594494434
 2189957.5268046702879.3976009842190066.70956857702937.166859669
#Sta/Elev= 30
       0 1446.47    26.3 1441.07    43.3 1438.78      47 1438.48    63.1 1438.38
    71.8 1437.85    86.6 1437.52   105.1  1437.7   109.9 1436.98     118 1433.65
     119 1433.27   123.6 1432.71   128.3  1432.9   131.5 1433.68   137.5 1436.14
   142.2 1437.03   146.8 1437.34     156 1437.85   180.3 1437.56   209.9 1438.14
   212.9 1438.53     224 1441.02   225.9  1441.2   234.5 1440.52   246.7 1441.87
   255.7 1443.29   260.2 1443.53   264.8 1444.17   273.8 1444.19   285.7 1443.59
#Mann= 5 ,-1,0
       0      .1       0   95.08     .05       0     118    .045       0
   131.5     .05       0  242.22     .07       0
Bank Sta=118,131.5
XS Rating Curve= 0 ,0
Exp/Cntr(USF)=0,0
Exp/Cntr=0.3,0.1

Type RM Length L Ch R = 1 ,2530    ,177,184.7,192.5
XS GIS Cut Line= 4
 2189747.9382695702843.0159569542189818.55775184702962.186333415
2189839.36527789703001.2792611422189882.24139217703090.814676261
#Sta/Elev= 30
       0 1444.46    21.1  1440.9    30.4 1439.85    39.7 1439.13      49 1438.61
    67.6 1437.95    76.9 1437.15    98.1 1435.79   112.7 1435.18     136 1435.45
   159.7 1435.32   187.1 1435.66   191.6 1435.25   195.3 1434.52   200.31432.827
   204.9 1431.47   210.3 1431.78   213.3 1432.31   215.11432.987   218.2 1434.25
   222.6 1436.59     227 1438.46   231.3 1438.96   240.3 1439.43   244.8 1439.95
     249 1441.07   253.7 1443.06   258.1 1443.96   271.4  1445.1   282.1 1445.48
#Mann= 5 ,-1,0
       0      .1       0      90     .06       0     110      .1       0
   200.3    .045       0   215.1      .1       0
Bank Sta=200.3,215.1
XS Rating Curve= 0 ,0
Exp/Cntr(USF)=0,0
Exp/Cntr=0.3,0.1

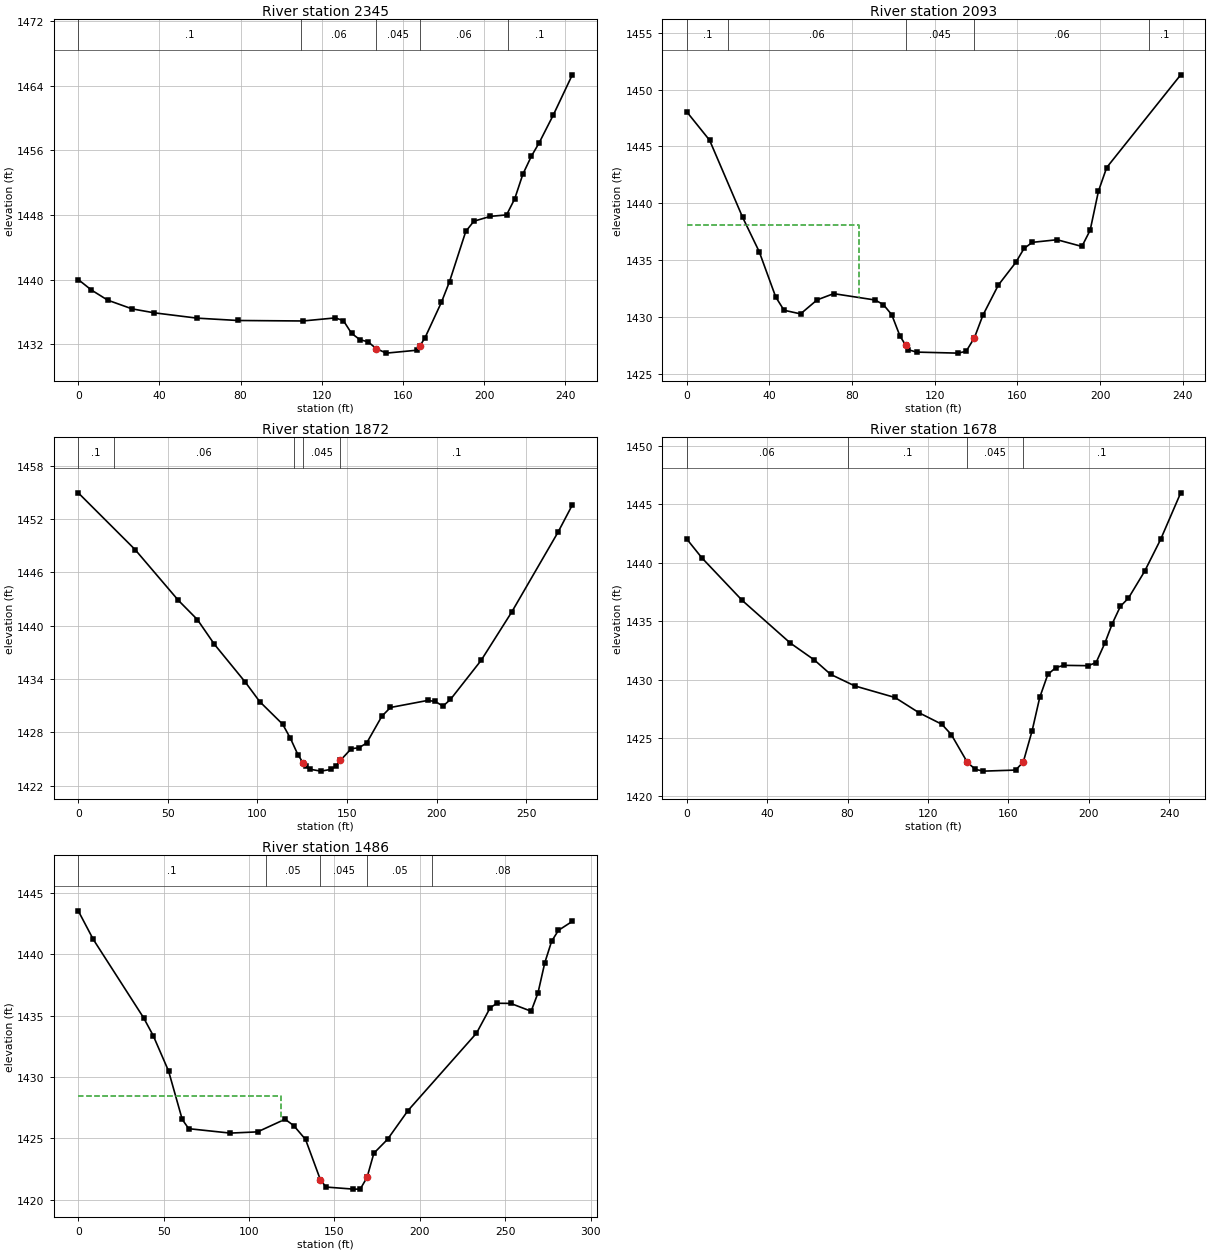
Type RM Length L Ch R = 1 ,2345    ,254.3,252.1,246.8
XS GIS Cut Line= 3
2189667.23028967702906.6995972852189674.16613169703028.392098115
2189662.18604093703149.454067853
#Sta/Elev= 30
       0 1440.02     6.5 1438.72    14.5 1437.47    26.5 1436.39    37.4  1435.9
    58.6 1435.24    78.6 1434.95   110.7 1434.89   126.7 1435.27   130.7 1434.93
   134.7 1433.36   138.8 1432.58   142.9  1432.3   146.8 1431.48   151.8 1430.91
   166.9 1431.27   168.3 1431.77   170.9 1432.81     179 1437.21     183 1439.77
     191 1445.98     195 1447.24   203.1 1447.84   211.1 1448.02   215.1    1450
   219.1 1453.04   223.3 1455.27   227.2 1456.96   234.2 1460.42   243.5 1465.36
#Mann= 5 ,-1,0
       0      .1       0     110     .06       0   146.8    .045       0
   168.3     .06       0  211.89      .1       0
Bank Sta=146.8,168.3
XS Rating Curve= 0 ,0
Exp/Cntr(USF)=0,0
Exp/Cntr=0.3,0.1

Type RM Length L Ch R = 1 ,2093    ,226,221.2,216.1
XS GIS Cut Line= 4
2189433.10557074702894.0389058292189434.50675095702985.816209276
2189436.60852125703047.4681383092189438.00970146703132.940130833
#Sta/Elev= 30
       0 1448.06    11.1 1445.55    27.1 1438.76    35.1 1435.75    43.1 1431.76
    47.1  1430.6    55.1 1430.28    63.1 1431.51    71.1 1432.06    91.2  1431.5
    95.2 1431.09    99.2 1430.21   103.2 1428.33     106 1427.51   107.2 1427.13
   111.2 1426.92   131.2 1426.83   135.2 1426.99   139.2 1428.18   143.3 1430.16
   150.8 1432.82   159.2  1434.8   163.2 1436.03   167.2 1436.57   179.2  1436.8
   191.2 1436.21   195.2 1437.64   199.2 1441.07   203.2 1443.15     239  1451.3
#Mann= 5 ,-1,0
       0      .1       0      20     .06       0     106    .045       0
   139.2     .06       0  223.48      .1       0
#XS Ineff= 2 , 0
           83.52 1438.12
Permanent Ineff=
       T       F
Bank Sta=106,139.2
XS Rating Curve= 0 ,0
Exp/Cntr(USF)=0,0
Exp/Cntr=0.3,0.1

Type RM Length L Ch R = 1 ,1872    ,188.4,194,201.5
XS GIS Cut Line= 3
2189189.69423689702901.7175271192189199.30452636702981.482929752
2189266.57655268703165.039458705
#Sta/Elev= 30
       0 1454.94    31.7 1448.56    55.9 1442.84    66.5 1440.68      76  1437.9
    93.3 1433.63   101.3 1431.45   114.1 1428.91   118.4 1427.34   122.6 1425.49
   125.4  1424.6   126.9 1424.16   129.4 1423.84   135.4 1423.63     141 1423.82
   143.9  1424.2   146.3 1424.83   152.4 1426.15   156.7 1426.26     161 1426.79
   169.5 1429.81   174.3 1430.79     195 1431.58   199.3 1431.47   203.6 1430.94
   207.8  1431.7   224.9 1436.09   241.9  1441.5   267.8  1450.5   275.8 1453.57
#Mann= 5 ,-1,0
       0      .1       0      20     .06       0  120.34      .1       0
   125.4    .045       0   146.3      .1       0
Bank Sta=125.4,146.3
XS Rating Curve= 0 ,0
Exp/Cntr(USF)=0,0
Exp/Cntr=0.3,0.1

Type RM Length L Ch R = 1 ,1678    ,191.4,192,192.5
XS GIS Cut Line= 3
2189031.36873857702933.5507870742189033.09859067703044.261321814
2189031.36873857703179.189786028
#Sta/Elev= 30
       0 1442.04     7.6 1440.41    27.6 1436.78    51.6 1433.12    63.5 1431.68
    71.6 1430.45    83.6 1429.46   103.6 1428.47   115.6 1427.16   126.9 1426.18
   131.6  1425.3   139.6 1422.92   143.6 1422.32   147.6 1422.17   163.6 1422.26
   167.4 1422.95   171.8 1425.62   175.6 1428.48   179.6 1430.44   183.6 1431.03
   187.6 1431.22   199.6 1431.19   203.6 1431.45     208 1433.13   211.7  1434.8
   215.7 1436.27   219.7 1436.97   227.7 1439.25   235.7 1441.99   245.7 1445.98
#Mann= 4 ,-1,0
       0     .06       0      80      .1       0   139.6    .045       0
   167.4      .1       0
Bank Sta=139.6,167.4
XS Rating Curve= 0 ,0
Exp/Cntr(USF)=0,0
Exp/Cntr=0.3,0.1

Type RM Length L Ch R = 1 ,1486    ,215.2,217.8,219.9
XS GIS Cut Line= 3
2188855.88559817702908.347844023 2188848.1012637703035.491973763
2188841.18185528 703197.23314561
#Sta/Elev= 30
       0 1443.55     8.8 1441.22    38.3 1434.82    43.9 1433.37    52.9 1430.48
    60.9 1426.53    64.7 1425.78      89 1425.42     105 1425.52   121.1 1426.55
   126.2 1426.03   133.1  1424.9   141.8 1421.61   145.1 1421.02   161.1 1420.85
   165.1 1420.85   169.1  1421.8   173.1 1423.78   181.1 1424.91   193.1 1427.26
   233.2 1433.57   241.2 1435.64   245.2 1436.01   253.2    1436   265.2 1435.36
   269.2 1436.85   273.2 1439.32   277.2 1441.07   281.2 1441.96   289.3 1442.69
#Mann= 5 ,-1,0
       0      .1       0     110     .05       0   141.8    .045       0
   169.1     .05       0  207.38     .08       0
#XS Ineff= 2 , 0
          118.99 1428.48
Permanent Ineff=
       F       F
Bank Sta=141.8,169.1
XS Rating Curve= 0 ,0
Exp/Cntr(USF)=0,0
Exp/Cntr=0.3,0.1