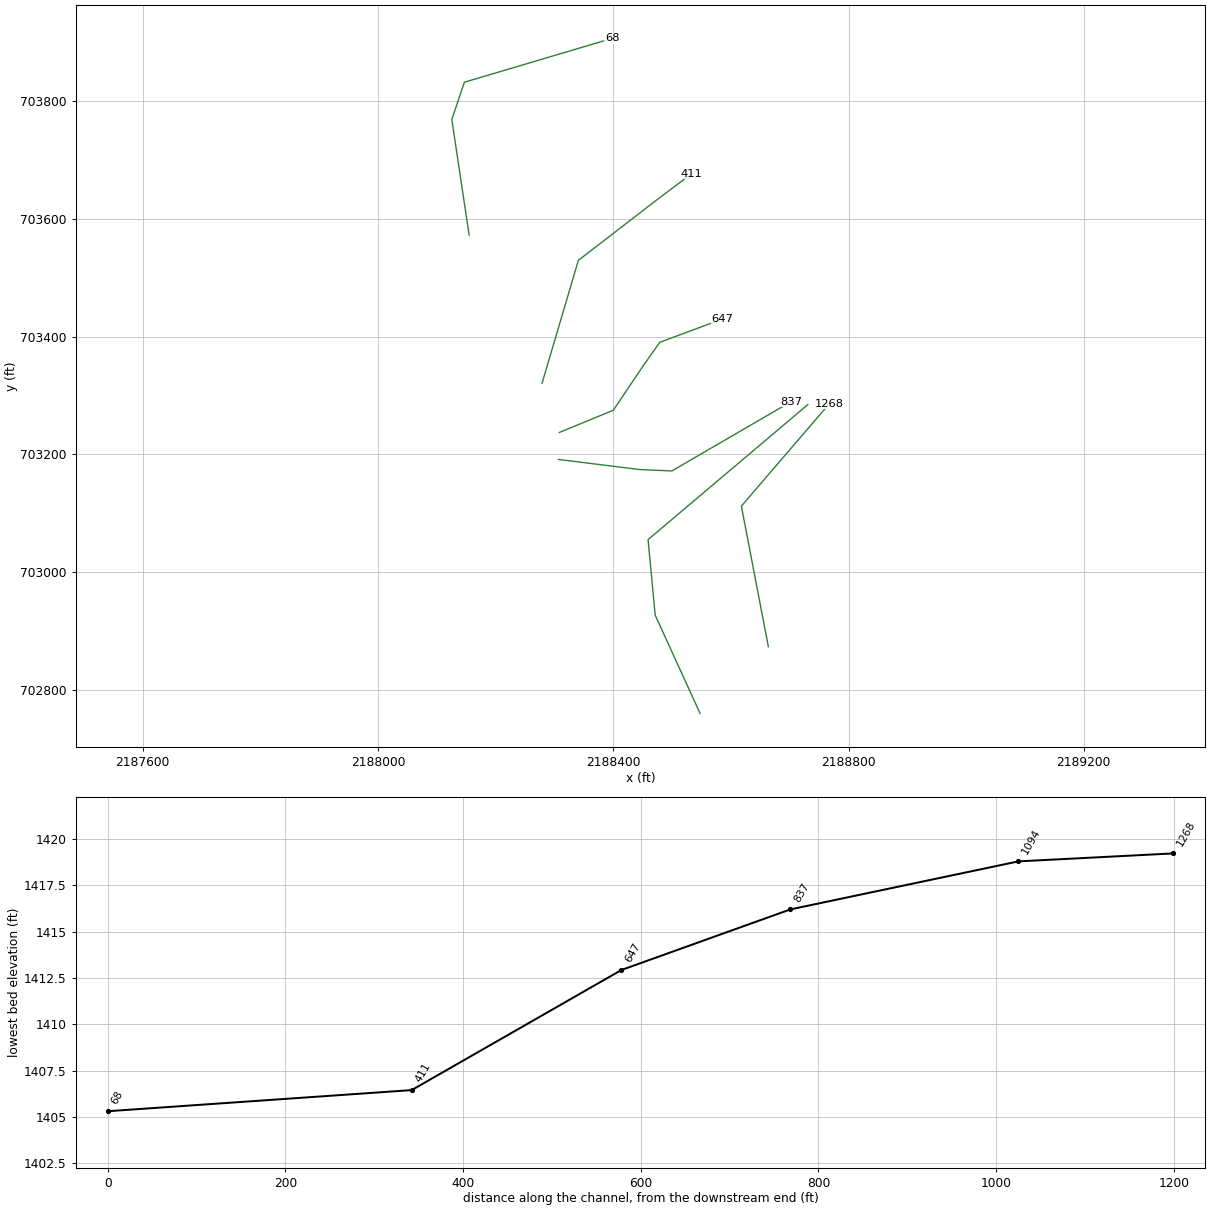
HEC-RAS study TRUBIERN.prj: TRUBIERN

--- TRUBIERN.g01 (geometry) --- (continued)

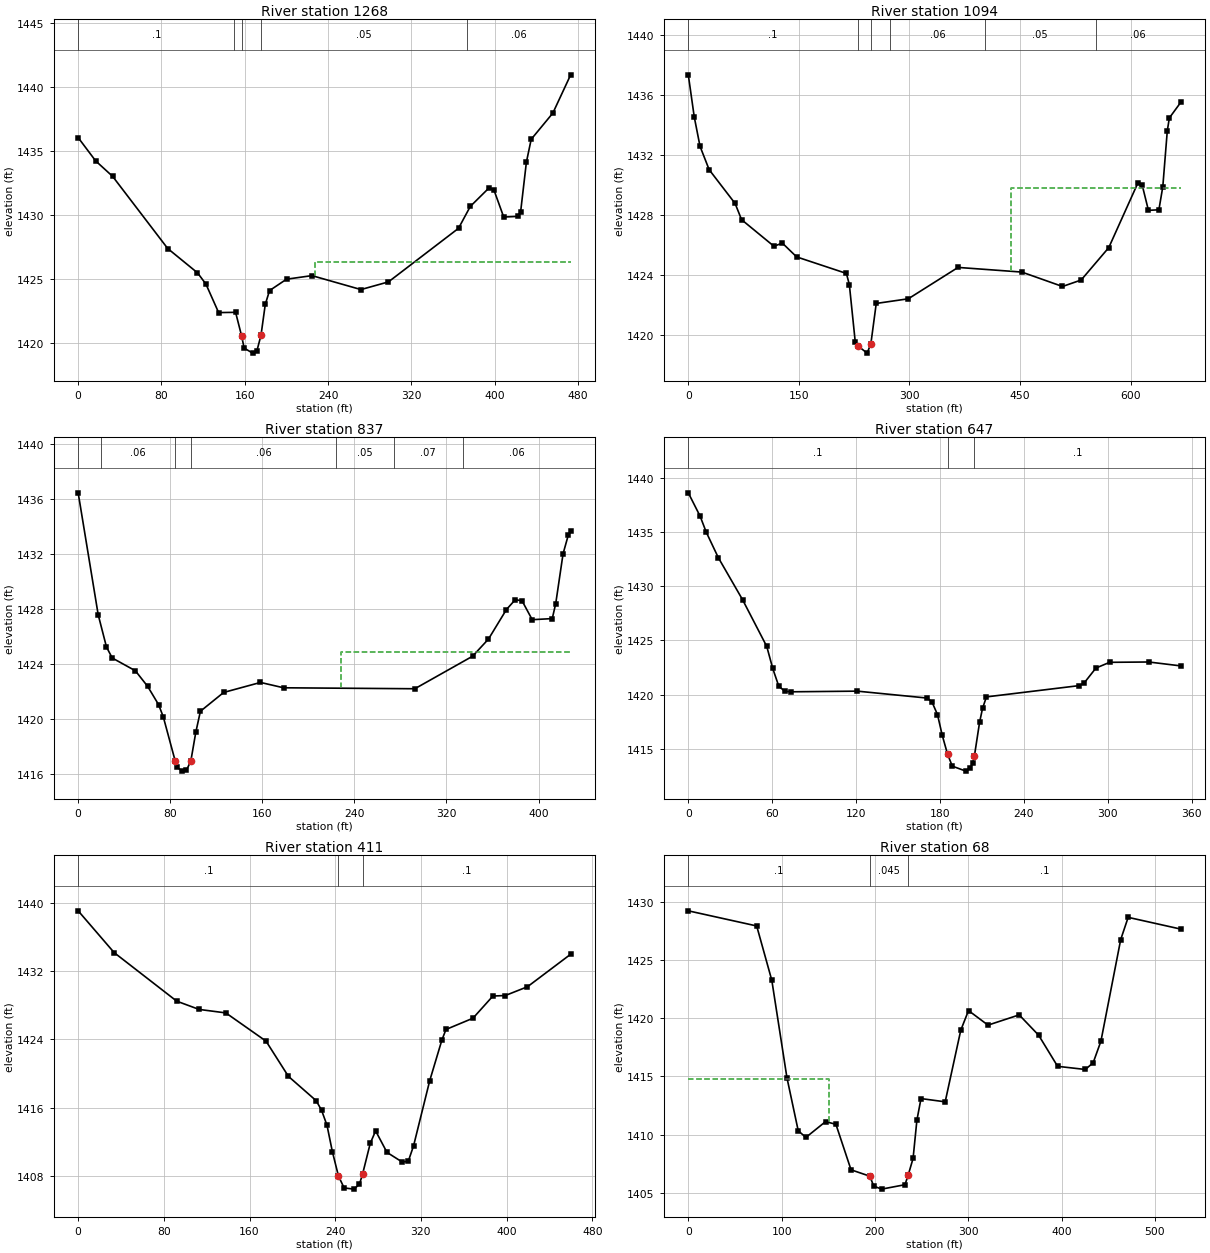
Type RM Length L Ch R = 1 ,1268    ,176.3,174.5,173.9
XS GIS Cut Line= 3
2188663.73319919702872.6829919752188617.81737171703111.872418882
2188767.31076352703285.925439355
#Sta/Elev= 30
       0 1436.07    16.8 1434.25    33.1 1433.04      86  1427.4   114.6  1425.5
   122.7 1424.62   134.9 1422.39   151.2 1422.41     1571420.556   159.4 1419.62
   167.5 1419.22   171.6 1419.38   175.6 1420.62   179.7 1423.03   183.8 1424.11
   200.1    1425   224.5 1425.28   271.6 1424.19     298 1424.79   365.3 1428.98
   376.6 1430.69   394.5 1432.13   399.3 1431.98   408.7 1429.86     422 1429.91
   424.9 1430.24   430.5 1434.16   435.1 1435.94   455.9 1437.99     473 1440.98
#Mann= 5 ,-1,0
       0      .1       0     150     .05       0     157    .045       0
   175.6     .05       0  373.56     .06       0
#XS Ineff= 2 , 0
                          227.04         1426.31
Permanent Ineff=
       F       F
Bank Sta=157,175.6
XS Rating Curve= 0 ,0
Exp/Cntr(USF)=0,0
Exp/Cntr=0.3,0.1

Type RM Length L Ch R = 1 ,1094    ,281.3,256.6,234.6
XS GIS Cut Line= 4
2188547.55517525702759.4507340492188471.26091307702926.541473531
2188459.18135582703054.8904452632188730.76727143703284.418466635
#Sta/Elev= 30
       0 1437.33     8.1 1434.52    15.9 1432.57    28.3 1431.01    63.5 1428.76
    72.3 1427.68   116.2 1425.91   127.6 1426.12     147  1425.2   214.5  1424.1
   218.5 1423.36   226.5 1419.54   230.5 1419.26   242.6 1418.79   247.7 1419.41
     255  1422.1   298.5 1422.41     366  1424.5   452.5 1424.19   507.7 1423.23
     533 1423.66   570.5 1425.82   610.1 1430.14   615.8 1429.99   624.3  1428.3
   638.5 1428.34   643.8 1429.88   649.9 1433.61   652.7 1434.46   668.2  1435.5
#Mann= 6 ,-1,0
       0      .1       0   230.5    .045       0   247.7      .1       0
  273.68     .06       0   402.6     .05       0   552.6     .06       0
#XS Ineff= 2 , 0
                          438.14         1429.77
Permanent Ineff=
       F       T
Bank Sta=230.5,247.7
XS Rating Curve= 0 ,0
Exp/Cntr(USF)=0,0
Exp/Cntr=0.3,0.1

Type RM Length L Ch R = 1 ,837     ,173.3,190.2,205.6
XS GIS Cut Line= 4
2188306.76927638 703191.209710572188445.16955377703173.990762714
2188499.65989509703171.6554623722188701.86749723703289.205832336
#Sta/Elev= 30
       0 1436.47    17.4 1427.59    24.6 1425.24    29.6 1424.44    49.7 1423.51
    60.4 1422.37    69.9 1421.04      74 1420.14    84.41416.909    86.1 1416.49
    90.1  1416.2    94.1 1416.27    97.91416.941   102.2 1419.03   106.2 1420.56
   126.4 1421.93   158.4 1422.66   178.5 1422.27   292.5  1422.2   342.7 1424.57
   356.5 1425.82   372.1 1427.97   379.8 1428.69   385.7  1428.6   394.5 1427.23
   411.9 1427.31   414.9 1428.39   421.3 1432.03   425.9 1433.41   427.9 1433.68
#Mann= 7 ,-1,0
       0      .1       0      20     .06       0    84.4    .045       0
    97.9     .06       0  224.01     .05       0  274.01     .07       0
  334.01     .06       0
#XS Ineff= 2 , 0
                          228.17         1424.87
Permanent Ineff=
       F       T
Bank Sta=84.4,97.9
XS Rating Curve= 0 ,0
Exp/Cntr(USF)=0,0
Exp/Cntr=0.3,0.1

Type RM Length L Ch R = 1 ,647     ,236,236.1,228.7
XS GIS Cut Line= 5
2188308.34001017703237.0817502332188400.11731362703274.913615776
2188451.96098122703351.9785270672188479.28399522703390.510982713
2188585.07310072703429.744028462
#Sta/Elev= 30
       0 1438.61     8.5 1436.44    12.8 1434.99    21.5 1432.62    38.8 1428.75
    56.1 1424.44    60.4  1422.4    64.7 1420.77      69  1420.3    73.5 1420.25
   120.9 1420.31     171 1419.67   174.3  1419.3   178.2 1418.15   181.6 1416.24
   185.4 1414.49   188.8 1413.39   198.5 1412.93   201.8 1413.24   203.4 1413.69
   204.6 1414.32   208.3 1417.43   210.4 1418.71   213.2 1419.78   279.5 1420.82
     283 1421.05   291.5 1422.44   301.3 1422.97   329.3    1423   352.2 1422.64
#Mann= 3 ,-1,0
       0      .1       0   185.4    .045       0   204.6      .1       0
Bank Sta=185.4,204.6
XS Rating Curve= 0 ,0
Exp/Cntr(USF)=0,0
Exp/Cntr=0.3,0.1

Type RM Length L Ch R = 1 ,411     ,342.2,342.2,342.2
XS GIS Cut Line= 4
2188278.97102223703320.9501664272188340.66670774703529.766332774
2188469.99035621703629.4285939862188532.87249722 703676.88681361
#Sta/Elev= 30
       0 1439.08    33.6 1434.18      92 1428.49   112.9 1427.52   137.9 1427.11
   175.4  1423.8   196.3 1419.67   222.2 1416.82   227.2 1415.71   232.3 1413.94
   237.3 1410.86     243 1407.99   248.3 1406.59   257.5 1406.45   262.6 1407.03
   265.5  1408.2   272.7 1411.82   277.7 1413.28   288.3 1410.76   302.5 1409.63
   308.2 1409.72   313.1 1411.51   328.2 1419.16   339.6 1423.94   343.4 1425.17
   368.6 1426.49   387.2 1429.09   398.8 1429.15   419.5 1430.18   459.8 1433.99
#Mann= 3 ,-1,0
       0      .1       0     243    .045       0   265.5      .1       0
Bank Sta=243,265.5
XS Rating Curve= 0 ,0
Exp/Cntr(USF)=0,0
Exp/Cntr=0.3,0.1

Type RM Length L Ch R = 1 ,68      ,,,
XS GIS Cut Line= 4
2188154.97039512703572.6919856482188125.43682353703769.224480254
2188146.91578469703832.5874156732188398.21963025703907.226805701
#Sta/Elev= 30
       0 1429.22    73.3 1427.92    89.5 1423.25   105.7 1414.89   117.8 1410.33
     126 1409.75   147.1 1411.11   158.2 1410.88   174.4 1406.97   194.6 1406.42
   198.7 1405.57   207.2 1405.31   232.2 1405.69   235.6  1406.5   240.9 1407.95
     245 1411.24   249.4 1413.09   275.3 1412.81     292 1418.96   300.3 1420.65
   321.2  1419.4   354.6 1420.28   375.4 1418.54   395.8 1415.86   425.5 1415.59
   433.9 1416.17   442.2 1418.02   463.4 1426.75   471.4 1428.66   527.8 1427.65
#Mann= 3 ,-1,0
       0      .1       0   194.6    .045       0   235.6      .1       0
#XS Ineff= 2 , 0
          150.42 1414.74
Permanent Ineff=
       T       F
Bank Sta=194.6,235.6
XS Rating Curve= 0 ,0
Exp/Cntr(USF)=0,0
Exp/Cntr=0.3,0.1
LCMann Table=0

Chan Stop Cuts=-1
Use User Specified Reach Order=0
Composite Channel Slope=5